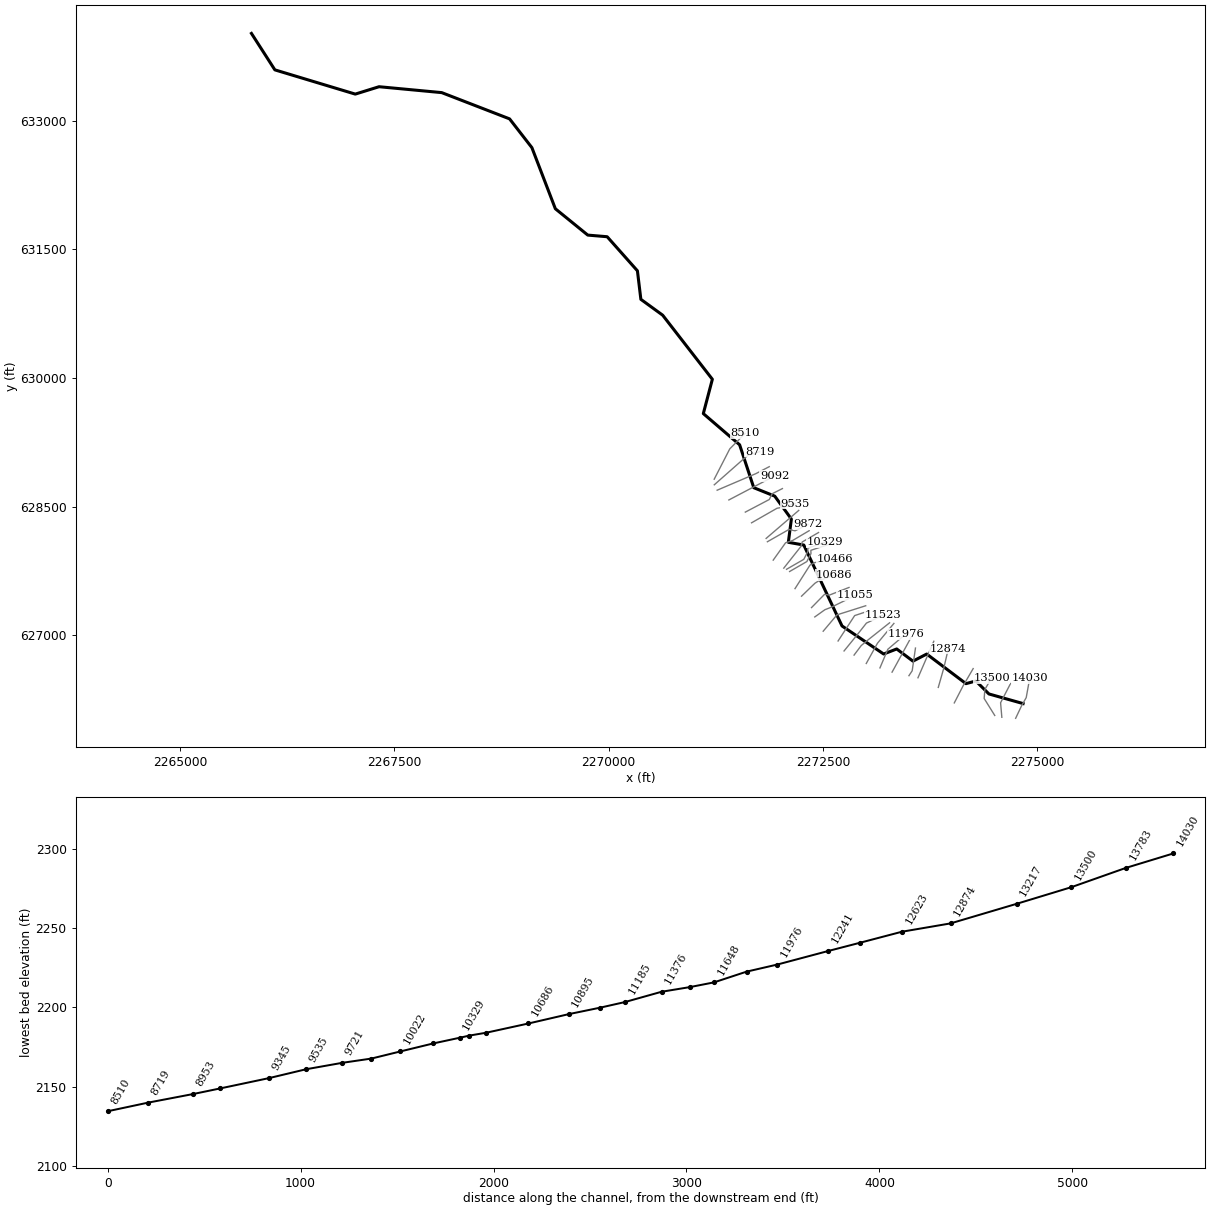
--- DRYRN.prj (project) ---

Proj Title=DRYRN
Current Plan=p01
Default Exp/Contr=0,0
English Units
Geom File=g01
Flow File=f01
Plan File=p01
BEGIN DESCRIPTION:
----------MODEL BY WOOD PLC 2022----------
AFH study
Randolph County, WV
HEC-RAS Version: RAS 6.2
Vertical Datum: NAVD88
Projection: NAD 1983 StatePlane West Virginia S FIPS 4702 (US Feet)
Terrain: 1-meter LIDAR (FEMA Region III 3DEP collected 2016-2018)
Land Use: 2019 NLCD
Hydrologic Method:
WV SIR2010-5033 regression equations
Additional Model Notes:
None
END DESCRIPTION:
DSS File=dss
DSS Export Rating Curves= 0
DSS Export Rating Curve Sorted= 0
DSS Export Volume Flow Curves= 0
DXF OffsetX= 0
DXF OffsetY= 0
DXF ScaleX= 0
DXF ScaleY= 0

--- DRYRN.p01 (plan) ---

Plan Title=Floodplain
Program Version=6.20
Short Identifier=Floodplain
Geom File=g01
Flow File=f01
Subcritical Flow
K Sum by GR= 0
Std Step Tol= 0.01
Critical Tol= 0.01
Num of Std Step Trials= 20
Max Error Tol= 0.3
Flow Tol Ratio= 0.001
Split Flow NTrial= 30
Split Flow Tol= 0.02
Split Flow Ratio= 0.02
Log Output Level= 0
Friction Slope Method= 1
Unsteady Friction Slope Method= 2
Unsteady Bridges Friction Slope Method= 1
Parabolic Critical Depth
Global Vel Dist= 0 , 0 , 0
Global Log Level= 0
CheckData=True
Encroach Param=-1 ,0,0, 0
Computation Interval=0.1SEC
Output Interval=1SEC
Instantaneous Interval=Max Profile
Mapping Interval=1HOUR
Computation Time Step Use Courant=        0
Computation Time Step Use Time Series=    0
Computation Time Step Count To Double=0
Computation Time Step Max Doubling=0
Computation Time Step Max Halving=0
Computation Time Step Residence Courant=0
Run HTab= 0
Run UNet= 0
Run Sediment= 0
Run PostProcess= 0
Run WQNet= 0
Run RASMapper=-1
UNET Theta= 0
UNET Theta Warmup= 0
UNET ZTol= 0
UNET ZSATol= 0
UNET MxIter= 0
UNET Max Iter WO Improvement= 0
UNET MaxInSteps= 0
UNET DtIC= 0
UNET DtMin= 0
UNET MaxCRTS= 0
UNET WFStab= 0
UNET SFStab= 0
UNET WFX= 1
UNET SFX= 1
UNET Gravity=32.174
UNET 1D Methodology=Finite Difference
UNET DSS MLevel= 1
UNET Pardiso=0
UNET DZMax Abort= 0
UNET Use Existing IB Tables= 0
UNET Froude Reduction=False
UNET Froude Limit= 0
UNET Froude Power= 0
UNET D1 Cores= 0
UNET WindReference=Eulerian
UNET WindDragFormulation=Hsu (1988)
UNET D2 Coriolis=0
UNET D2 Cores= 0
UNET D2 Theta= 1
UNET D2 Theta Warmup= 1
UNET D2 Z Tol= 0.01
UNET D2 Volume Tol= 0.01
UNET D2 Max Iterations= 20
UNET D2 Equation= 0
UNET D2 RampUpFraction=0.1
UNET D2 TimeSlices= 1
UNET D2 Turbulence Formulation=Non-Conservative (original)
UNET D2 Eddy Viscosity=0.3
UNET D2 Transverse Eddy Viscosity=0.1
UNET D2 Smagorinsky Mixing=0
UNET D2 BCVolumeCheck=0
UNET D2 Cores=0
UNET D2 SolverType=PARDISO (Direct)
UNET D2 Minimum Iterations= 2147483647
UNET D2 Maximum Iterations= 2147483647
UNET D2 Restart Number= 10
UNET D2 Relaxation Coeff=1.3
UNET D2 SOR Precondition Iterations= 10
UNET D2 ILUT Maximum Fill= 8
UNET D2 ILUT Tolerance=1E-08
UNET D1D2 MaxIter= 0
UNET D1D2 ZTol=0.01
UNET D1D2 QTol=0.1
UNET D1D2 MinQTol=1
DSS File=dss
Write IC File= 0
Write IC File at Fixed DateTime=0
Write IC File at Sim End=0
Echo Input=False
Echo Parameters=False
Echo Output=False
Write Detailed= 0
HDF Write Warmup=0
HDF Write Time Slices=0
HDF Flush=0
HDF Compression= 1
HDF Chunk Size= 1
HDF Spatial Parts= 1
HDF Use Max Rows=0
HDF Fixed Rows= 1
Calibration Method= 0
Calibration Iterations= 20
Calibration Max Change=0.05
Calibration Tolerance=0.2
Calibration Maximum=1.5
Calibration Minimum=0.5
Calibration Optimization Method= 1
WQ AD Non Conservative
WQ ULTIMATE=-1
WQ Max Comp Step=1HOUR
WQ Output Interval=15MIN
WQ Output Selected Increments= 0
WQ Output face flow=0
WQ Output face velocity=0
WQ Output face area=0
WQ Output face dispersion=0
WQ Output cell volume=0
WQ Output cell surface area=0
WQ Output cell continuity=0
WQ Output cumulative cell continuity=0
WQ Output face conc=0
WQ Output face dconc_dx=0
WQ Output face courant=0
WQ Output face peclet=0
WQ Output face adv mass=0
WQ Output face disp mass=0
WQ Output cell mass=0
WQ Output cell source sink temp=0
WQ Output nsm pathways=0
WQ Output nsm derived pathways=0
WQ Create Restart=0
WQ Fixed Restart=0
WQ System Summary=0
WQ Write To DSS=0
Sorting and Armoring Iterations= 10
XS Update Threshold= 0.02
Bed Roughness Predictor= 0
Hydraulics Update Threshold= 0.02
Energy Slope Method= 1
Volume Change Method= 1
Sediment Retention Method= 0
Sediment TS Multiplier= 1
Warm Up Method= 0
XS Weighting Method= 0
Number of US Weighted Cross Sections= 1
Number of DS Weighted Cross Sections= 1
Upstream XS Weight=0
Main XS Weight=1
Downstream XS Weight=0
Number of DS XS's Weighted with US Boundary= 1
Upstream Boundary Weight= 1
Weight of XSs Associated with US Boundary= 0
Number of US XS's Weighted with DS Boundary= 1
Downstream Boundary Weight= 0.5
Weight of XSs Associated with DS Boundary= 0.5
Percentile Method= 0
Sediment Output Level= 3
Mass or Volume Output= 0
Output Increment Type= 1
Profile and TS Output Increment= 1
Transport Output Increment 1
XS Output Flag= 0
XS Output Increment= 10
Read HDF5 Sediment Hotstart= 0
Sediment Hotstart Type= 0
Write Gradation File= 0
Read Gradation Hotstart= 0
Write HDF5 File= 1
Write Binary Output= 1
Write DSS Sediment File= 0
DSS Sediment Output Type= 1
SV Curve= 0
Specific Gage Flag= 0
Subcell Erosion Methods= 0
Subcell Deposition Methods= 0
Advection Scheme= 1
Matrix Solver= 0
Implicit Weighting Factor= 1
Maximum Outer Loop Convergence Iterations= 5
Convergence Maximum Absolute= 0.001
Convergence RMSE= 0.0001
Grain Fractions Max Abs Error= 0.001
Max Subgrid Regions= 1
Max Subgrid Length Scale= 3.402823E+38
Initial Layer Thickness= 3.402823E+38
Min Layer Thickness= 3.402823E+38
Max Layer Thickness= 3.402823E+38
Number of Layers= 5

--- DRYRN.f01 (steady flow) ---

Flow Title=Flow
Program Version=6.20
Number of Profiles= 1
Profile Names=P100yr
River Rch & RM=DRYRN,Main,14030
     403
River Rch & RM=DRYRN,Main,7727
     596
River Rch & RM=DRYRN,Main,3011
     673
Boundary for River Rch & Prof#=DRYRN,Main            , 1
Up Type= 0
Dn Type= 3
Dn Slope=0.00942
DSS Import GetInterval= 0
DSS Import GetPeak= 0
DSS Import FillOption= 0

--- DRYRN.g01 (geometry) ---

Geom Title=Geometry
Program Version=6.20

River Reach=DRYRN           ,Main
Reach XY= 30
     2274835.423      626203.535     2274436.767      626315.706
     2274284.468      626466.903     2274169.017      626436.087
     2273711.233      626781.313     2273550.434        626698.5
     2273361.169      626840.486     2273208.629      626781.833
     2272723.212      627108.917     2272277.379      628052.667
     2272097.171      628084.438     2272132.587      628355.792
2271938.59612137628623.058169917     2271694.045      628721.417
     2271528.941      629221.938     2271105.568      629585.737
2271210.97823466629986.123767501     2270631.456      630733.561
     2270377.067      630918.4572270336.93409628631251.144144425
     2269984.045      631648.669     2269757.881      631667.664
      2269379.77      631974.993     2269106.141      632687.675
     2268845.815      633023.297     2268054.422      633329.507
     2267323.524      633398.328     2267046.089      633312.146
     2266108.285      633594.784     2265835.173      634020.023

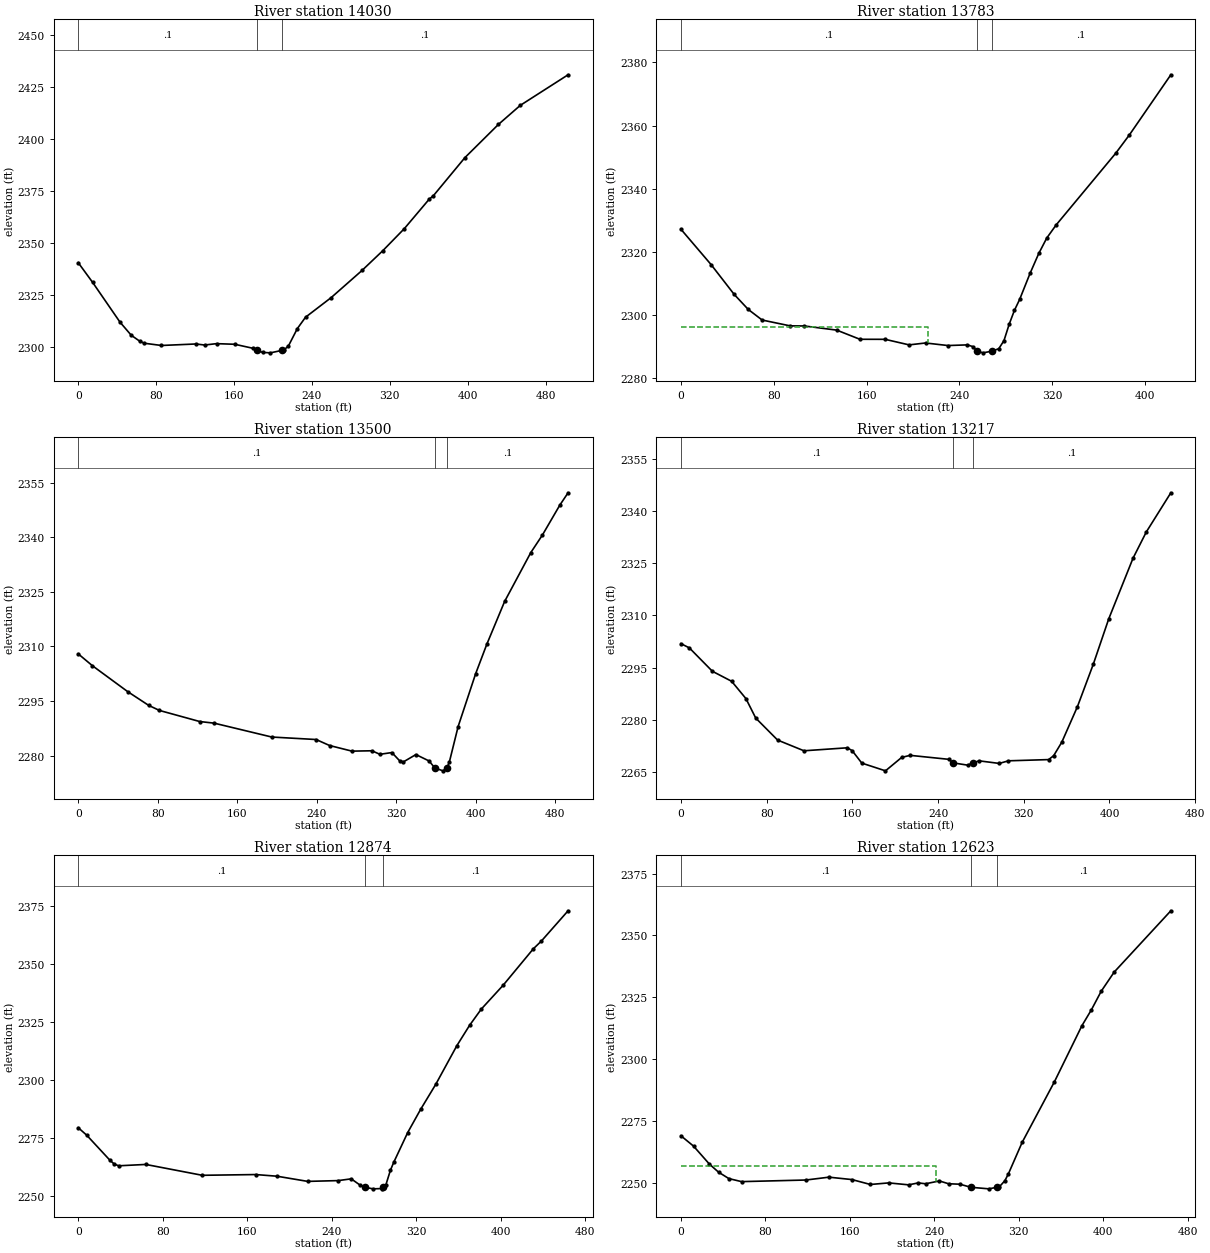
Type RM Length L Ch R = 1 ,14030   ,244.2,246.3,247.4
XS GIS Cut Line= 4
2274748.27525655626031.8837576962274817.63324147626178.367437203
 2274871.5759744626273.1242926152274912.92699685626501.490559722
#Sta/Elev= 30
       0 2340.54    14.7 2331.13    42.9 2311.95    54.5 2305.62    63.4 2302.71
    67.8  2301.8    85.5 2300.72   120.9 2301.44   129.8 2300.94   142.1  2301.6
   160.8  2301.3   179.1 2299.41   183.22298.425   189.5 2297.38   197.5 2297.18
   209.52298.391   211.3 2298.56   215.9 2300.46   225.1 2308.86   233.5 2314.31
   259.9 2323.77   291.5 2336.79     313 2346.36     335 2356.92   360.6 2371.11
   364.7 2372.67   397.2 2391.05   431.6 2407.01   454.1 2416.19   503.2  2430.9
#Mann= 3 ,-1,0
       0      .1       0   183.2    .045       0   209.5      .1       0
Bank Sta=183.2,209.5
XS Rating Curve= 0 ,0
Exp/Cntr=0.3,0.1

Type RM Length L Ch R = 1 ,13783   ,283.7,283.2,281.8
XS GIS Cut Line= 3
2274587.23144834626043.4036764832274572.73245259626213.318161224
2274688.55958729 626436.99355425
#Sta/Elev= 30
       0 2327.15    25.9    2316    45.9 2306.53      58 2301.78      70 2298.42
    94.1 2296.58   106.2 2296.55   134.3 2295.23   154.3 2292.33     176 2292.32
   196.7 2290.56   210.9 2291.16   230.2 2290.35     247 2290.56   251.5 2290.03
   255.6 2288.56   260.5 2288.04   267.9 2288.56     274 2289.34   278.5  2291.9
     283  2297.1   287.5 2301.47     292 2304.93     301  2313.2   308.5 2319.49
   315.4 2324.38   323.5 2328.53   374.8 2351.19   386.7 2357.05   422.4 2376.06
#Mann= 3 ,-1,0
       0      .1       0   255.6    .045       0   267.9      .1       0
#XS Ineff= 2 , 0
          212.99 2296.29
Permanent Ineff=
       F       F
Bank Sta=255.6,267.9
XS Rating Curve= 0 ,0
Exp/Cntr=0.3,0.1

Type RM Length L Ch R = 1 ,13500   ,284.2,283.7,281.7
XS GIS Cut Line= 4
2274504.56817908626065.0410501982274381.04018441626263.078093285
2274389.44244773626368.1176012682274466.99912871 626501.63256125
#Sta/Elev= 30
       0 2307.97    14.3 2304.71    49.7 2297.62    70.9 2293.83    81.7 2292.44
   122.3 2289.39   136.9 2288.94   194.9 2285.13   239.5 2284.45   253.1  2282.8
   275.6 2281.26   295.7 2281.36   303.7 2280.39   315.8 2280.87   323.7 2278.58
   327.4 2278.31     340 2280.32   353.3 2278.55   359.1 2276.62   367.3 2275.85
  371.13 2276.63   373.7 2278.32   382.5 2288.02   400.1  2302.5   411.4 2310.63
   429.3 2322.36   455.7  2335.8   467.4 2340.62   484.9 2348.82   493.2  2352.2
#Mann= 3 ,-1,0
       0      .1       0   359.1    .045       0  371.13      .1       0
Bank Sta=359.1,371.13
XS Rating Curve= 0 ,0
Exp/Cntr(USF)=0,0
Exp/Cntr=0.3,0.1

Type RM Length L Ch R = 1 ,13217   ,338.2,342.4,343
XS GIS Cut Line= 3
2274032.61853136626211.1498970222274135.74886003626410.897059935
   2274252.99176626611.729805255
#Sta/Elev= 30
       0 2301.87     7.8 2300.66    29.3 2293.94    47.3 2291.06    60.6  2286.1
    69.8 2280.49    90.2 2274.18   114.8  2271.1   155.3 2271.96   159.8 2271.14
   168.8 2267.56   190.9 2265.34     206 2269.19   213.9 2269.79   250.2 2268.64
  253.95 2267.63   267.7 2266.97   272.32267.627   278.4 2268.21   297.1 2267.47
   305.7 2268.22   343.2 2268.57   347.9 2269.69   355.5 2273.57   370.1 2283.78
   384.9 2295.96   399.3 2308.98     422 2326.42   434.4 2333.96   457.3 2345.21
#Mann= 3 ,-1,0
       0      .1       0  253.95    .045       0   272.3      .1       0
Bank Sta=253.95,272.3
XS Rating Curve= 0 ,0
Exp/Cntr(USF)=0,0
Exp/Cntr=0.3,0.1

Type RM Length L Ch R = 1 ,12874   ,250.4,251.4,249.6
XS GIS Cut Line= 3
2273845.98803659626392.2280539032273910.31884591626617.385886493
2273962.58762847 626841.20349389
#Sta/Elev= 30
       0 2279.41       8 2276.19    30.1 2265.31    34.3 2263.64    38.4 2262.95
      64 2263.53   117.5 2258.84   168.1 2259.16   188.2 2258.45   217.3 2256.21
   246.3 2256.55   258.6 2257.31   266.8 2254.65  271.94 2253.65   279.1 2252.99
   287.4  2253.1   288.8 2253.68   291.5 2254.84   295.7    2261   298.8 2264.39
   312.1 2277.32   324.3 2287.31   338.6  2298.1   358.7 2314.89   370.7 2323.64
   381.8 2330.66   402.4 2340.91   431.1 2356.71   438.7 2360.05     464 2373.13
#Mann= 3 ,-1,0
       0      .1       0  271.94    .045       0   288.8      .1       0
Bank Sta=271.94,288.8
XS Rating Curve= 0 ,0
Exp/Cntr(USF)=0,0
Exp/Cntr=0.3,0.1

Type RM Length L Ch R = 1 ,12623   ,206.1,218.7,215.2
XS GIS Cut Line= 2
2273609.14505814626504.5275268112273793.79830709626930.421310679
#Sta/Elev= 30
       0 2269.15    11.9 2264.99    26.9 2257.75    35.6 2254.48    45.4 2251.88
    57.4 2250.66   118.4 2251.31   140.2 2252.46     162 2251.49   179.5 2249.51
   196.9 2250.15   215.7 2249.36   224.8 2250.14   231.8  2249.8   244.9 2250.93
   253.6  2249.8   264.3 2249.62  274.72 2248.38   291.7 2247.75   299.2 2248.37
   301.5  2248.5   306.9 2251.01   310.3 2253.84   323.3 2266.51   353.9 2290.98
   379.9 2313.57     389 2320.07   398.2 2327.49   410.5 2335.23   464.2 2359.97
#Mann= 3 ,-1,0
       0      .1       0  274.72    .045       0   299.2      .1       0
#XS Ineff= 2 , 0
          241.94 2256.88
Permanent Ineff=
       T       F
Bank Sta=274.72,299.2
XS Rating Curve= 0 ,0
Exp/Cntr=0.3,0.1

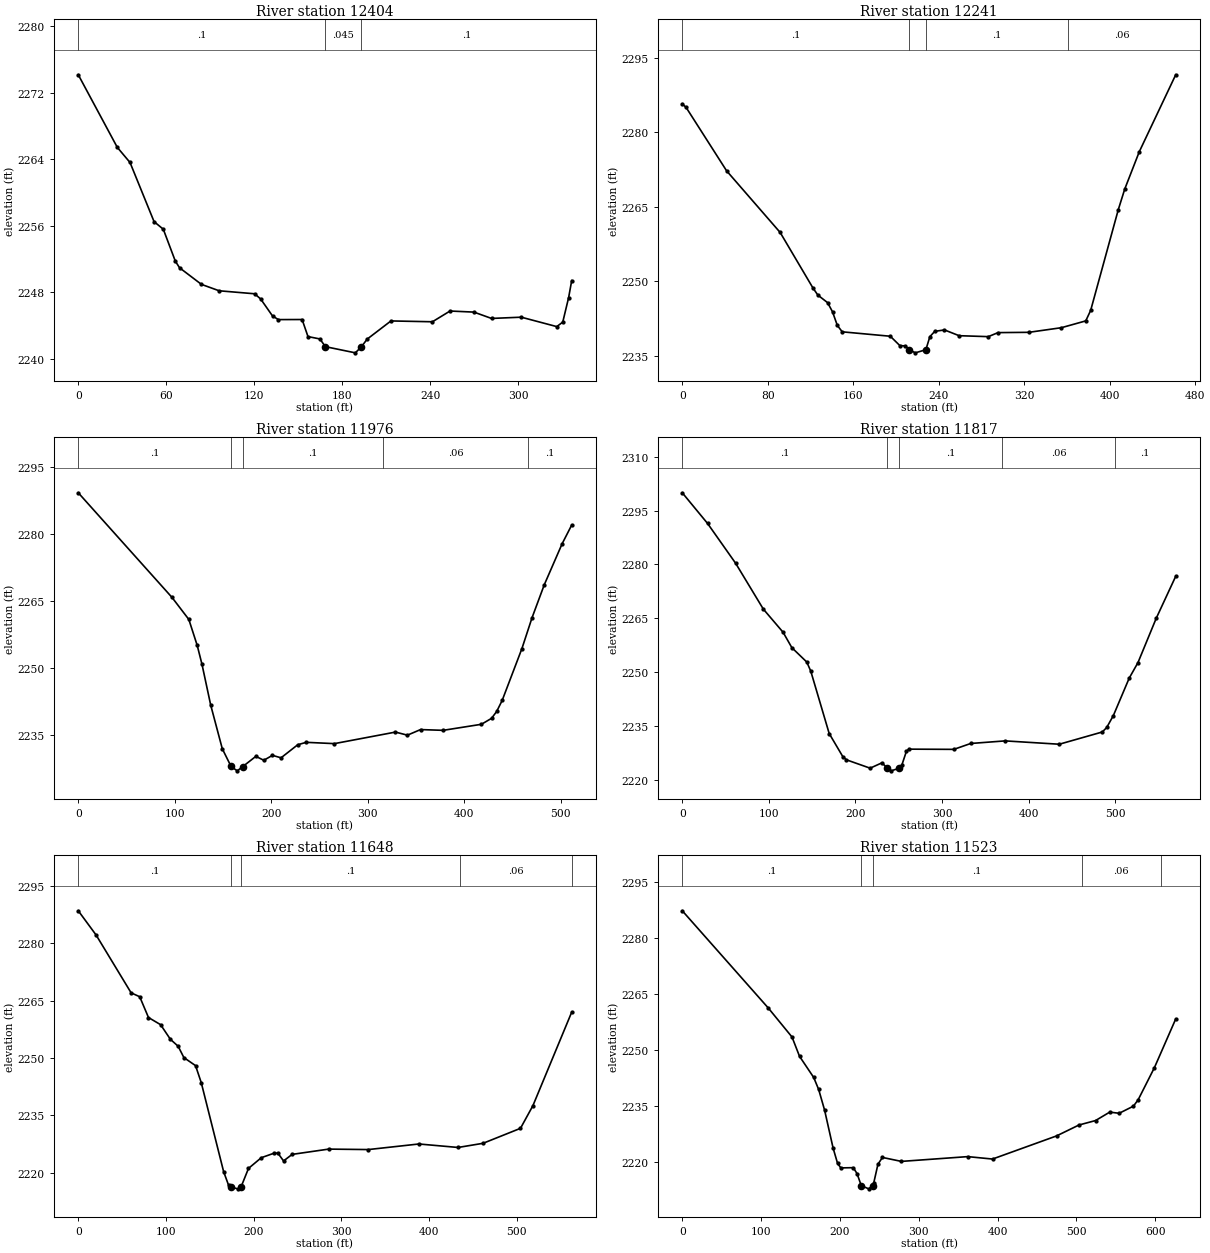
Type RM Length L Ch R = 1 ,12404   ,167.7,163.3,159.1
XS GIS Cut Line= 3
2273503.67663216 626528.826256322273541.78057465626586.470682138
2273579.88451714626851.244231238
#Sta/Elev= 30
       0 2274.13    26.6 2265.42    35.3  2263.6    51.7  2256.5      58 2255.59
    66.2 2251.76    69.1 2250.96      84 2248.97    96.1  2248.2   120.3 2247.84
   124.4 2247.22   132.5 2245.18   136.5 2244.74   152.7 2244.75   156.7  2242.7
   164.8 2242.42   168.6 2241.49     189 2240.75   193.1 2241.47   197.1  2242.4
   213.3 2244.58   241.6 2244.48   253.6 2245.77   269.9 2245.64   281.9 2244.88
   302.2 2245.03   326.4  2243.9   330.5 2244.44   334.5 2247.38   336.6 2249.42
#Mann= 3 ,-1,0
       0      .1       0   168.6    .045       0   193.1      .1       0
Bank Sta=168.6,193.1
XS Rating Curve= 0 ,0
Exp/Cntr(USF)=0,0
Exp/Cntr=0.3,0.1

Type RM Length L Ch R = 1 ,12241   ,262.6,264.7,266.2
XS GIS Cut Line= 3
2273306.84981994626570.0496474062273336.63260203626623.658655165
 2273528.7315465626975.095483812
#Sta/Elev= 30
       0  2285.7     3.6 2284.98    41.5 2272.22    91.6 2259.82   122.3 2248.64
   126.9 2247.21     136 2245.69   140.6 2243.85   145.1 2241.11   149.7 2239.82
   194.7 2238.93   203.6 2237.05   208.9 2236.98   212.4 2236.22   218.1 2235.59
  227.97 2236.22   231.7 2238.84   236.3 2239.92   245.4  2240.2   259.1 2239.04
   286.4 2238.85   295.5 2239.66   324.4 2239.72   354.8 2240.65   377.6 2242.02
   382.2 2244.13   408.1 2264.44   414.1 2268.56   427.7 2276.07   461.8 2291.56
#Mann= 4 ,-1,0
       0      .1       0   212.4    .045       0  227.97      .1       0
  361.33     .06       0
Bank Sta=212.4,227.97
XS Rating Curve= 0 ,0
Exp/Cntr=0.3,0.1

Type RM Length L Ch R = 1 ,11976   ,161.8,159.2,160.9
XS GIS Cut Line= 3
2273165.62627058626619.6895037972273257.75017612626837.046654776
2273467.44093849627015.554784579
#Sta/Elev= 30
       0 2289.14    97.2 2265.75   114.6 2260.84   123.3 2255.03   128.2 2250.85
   137.3 2241.68   149.3 2231.94  158.42 2227.98   164.8 2227.01   170.5 2227.96
   184.1 2230.25   192.3 2229.37   201.3 2230.47   210.2 2229.92   227.5 2232.84
   236.3 2233.38   265.5 2233.09   328.8 2235.67   341.2 2234.98   354.8 2236.23
   378.2 2236.06   417.9 2237.41   428.4 2238.74   433.7 2240.27   439.4 2242.73
   459.9 2254.33   470.4 2261.23   483.1  2268.6   501.6 2277.76   511.5 2281.93
#Mann= 5 ,-1,0
       0      .1       0  158.42    .045       0   170.5      .1       0
  316.07     .06       0  466.07      .1       0
Bank Sta=158.42,170.5
XS Rating Curve= 0 ,0
Exp/Cntr(USF)=0,0
Exp/Cntr=0.3,0.1

Type RM Length L Ch R = 1 ,11817   ,170.3,169.1,166
XS GIS Cut Line= 3
2273006.04372085626671.3111065072273136.55839749626907.254305845
2273328.23991255627138.501206251
#Sta/Elev= 30
       0 2299.96    29.2 2291.42    61.6 2280.34    93.6 2267.57   116.4 2261.13
   126.6 2256.82   143.8 2252.83   148.4 2250.31   169.7 2232.92   185.4  2226.5
   189.6  2225.6     217 2223.27   230.7 2224.77  236.92 2223.24   241.3 2222.53
   250.32223.241   253.6 2224.11     259 2228.04   261.9 2228.57   313.7 2228.51
   333.2 2230.15     373 2230.87   435.5 2229.94   485.2 2233.35   490.3  2234.6
     498 2237.94   516.3 2248.36   526.4 2252.67   547.5 2265.02     570  2276.7
#Mann= 5 ,-1,0
       0      .1       0  236.92    .045       0   250.3      .1       0
  369.64     .06       0  499.64      .1       0
Bank Sta=236.92,250.3
XS Rating Curve= 0 ,0
Exp/Cntr(USF)=0,0
Exp/Cntr=0.3,0.1

Type RM Length L Ch R = 1 ,11648   ,123.7,124.7,126.4
XS GIS Cut Line= 4
2272863.72580315626769.1742012592272946.83057853626879.672728639
2273006.17275979626929.8210508312273277.92126502627145.568043169
#Sta/Elev= 30
       0 2288.53    20.3  2282.2    60.3 2267.05    70.1 2266.03    80.1 2260.59
    93.9 2258.72   105.1 2254.89   113.9 2253.08   120.5  2250.1   133.8    2248
   140.3 2243.55   165.8 2220.27   171.4 2216.74  173.98 2216.23   181.9 2215.75
   185.7 2216.24   194.2  2221.1   208.8  2223.9   223.6  2225.1   227.8 2225.07
   234.2 2223.05     244 2224.77   285.7 2226.15   330.9 2226.03   388.6 2227.49
   433.3 2226.58   461.8 2227.67   504.5 2231.59   518.7 2237.53   562.9 2261.98
#Mann= 5 ,-1,0
       0      .1       0  173.98    .045       0   185.7      .1       0
  435.96     .06       0  562.93      .1       0
Bank Sta=173.98,185.7
XS Rating Curve= 0 ,0
Exp/Cntr(USF)=0,0
Exp/Cntr=0.3,0.1

Type RM Length L Ch R = 1 ,11523   ,146.5,147,147.7
XS GIS Cut Line= 4
2272746.93351667626817.246738742     2272893.816      626997.638
2273007.84437054627142.1156147772273196.48360558627232.493165963
#Sta/Elev= 30
       0 2287.26   108.9 2261.26   139.2 2253.44   148.7 2248.28   166.7 2242.61
     173 2239.39   180.5 2233.87   191.3  2223.7     197 2219.58   201.1 2218.39
   216.9 2218.45   221.7 2216.85     2272213.662   236.4 2212.78   241.42213.646
   242.9  2214.4   248.2 2219.38   253.9 2221.19   277.9 2220.13   362.1 2221.41
   393.5 2220.76   474.7 2226.95   503.2 2229.88   524.2 2231.07   542.2 2233.33
   554.2 2233.02   572.2 2234.92   578.2 2236.61   598.9 2245.25   625.9 2258.28
#Mann= 5 ,-1,0
       0      .1       0     227    .045       0   241.4      .1       0
  506.68     .06       0  606.68      .1       0
Bank Sta=227,241.4
XS Rating Curve= 0 ,0
Exp/Cntr=0.3,0.1

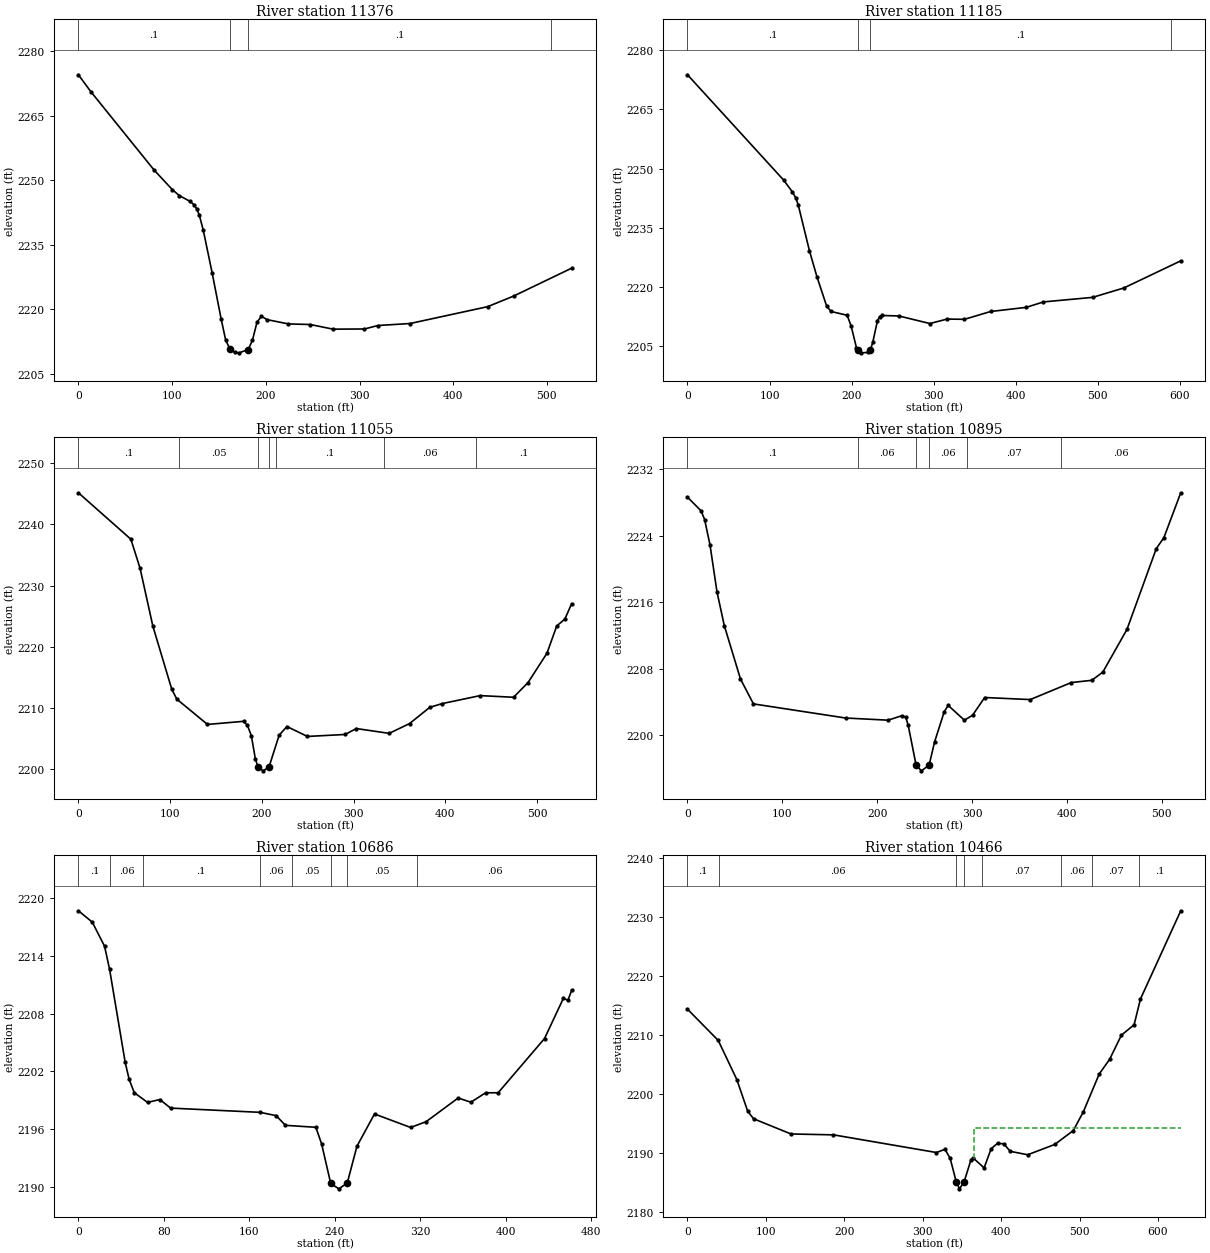
Type RM Length L Ch R = 1 ,11376   ,191.7,190.6,188.3
XS GIS Cut Line= 3
2272677.28233037626933.5862845472272870.77228988627229.875178613
2273034.48750838627284.258339262
#Sta/Elev= 30
       0 2274.52    13.4 2270.56    80.7 2252.38   100.4 2247.77   107.7 2246.42
   118.9  2245.1   123.7 2244.25   126.1 2243.37     129 2241.91   133.3 2238.33
   142.8 2228.36   152.4 2217.64   157.2 2212.78   161.62210.767   166.7 2209.94
   171.5 2209.83   181.22210.593   185.8 2212.78   190.6 2216.97   195.4 2218.34
   201.2 2217.56   224.1 2216.56   247.5 2216.42   271.8 2215.34   305.3 2215.38
   319.7 2216.19   353.9 2216.65   436.7 2220.57   464.5 2223.04   526.4 2229.53
#Mann= 4 ,-1,0
       0      .1       0   161.6    .045       0   181.2      .1       0
  503.87     .06       0
Bank Sta=161.6,181.2
XS Rating Curve= 0 ,0
Exp/Cntr(USF)=0,0
Exp/Cntr=0.3,0.1

Type RM Length L Ch R = 1 ,11185   ,132.3,130,125.2
XS GIS Cut Line= 3
2272503.58914523627047.5724372962272664.32836352627238.233232312
2272999.63379726627344.608937034
#Sta/Elev= 30
       0  2273.8   117.2  2247.1   127.7 2244.16   132.1 2242.55     135  2240.8
   148.6 2229.22   157.7 2222.66   169.5 2215.22   174.8 2213.81   194.6 2212.83
   199.5 2210.09   205.9 2204.62  207.88 2204.08   211.9 2203.31   220.1 2203.43
     223 2204.06   225.8 2205.97   231.5 2211.41   234.3 2212.52   236.7 2212.78
   257.6 2212.66   295.4 2210.74   316.4 2211.87   337.6 2211.81   369.5 2213.79
   412.9 2214.84   433.9 2216.22   493.7 2217.37   531.9 2219.76   601.2 2226.63
#Mann= 4 ,-1,0
       0      .1       0  207.88    .045       0     223      .1       0
  589.38     .06       0
Bank Sta=207.88,223
XS Rating Curve= 0 ,0
Exp/Cntr=0.3,0.1

Type RM Length L Ch R = 1 ,11055   ,163.8,160.6,156.7
XS GIS Cut Line= 4
2272405.64548805 627214.028406392272523.85335016627298.462593611
2272596.62812856627326.8286015182272878.81164406627464.986082863
#Sta/Elev= 30
       0 2245.16    57.2 2237.57    67.2 2232.84    81.1 2223.41   101.8 2213.04
   107.3 2211.44   140.7 2207.31     180 2207.82   184.2 2207.17   188.5 2205.47
   192.8 2201.74  195.62 2200.41   201.4 2199.73   207.8 2200.38   218.8 2205.56
   227.3 2206.97   249.6 2205.35   290.6 2205.67     303 2206.64   338.7 2205.85
   360.9 2207.45     383 2210.11   396.6 2210.72   437.9 2212.02   474.3 2211.75
   490.1 2214.16   510.7 2218.95   521.3 2223.39   530.2 2224.53   537.6 2227.04
#Mann= 7 ,-1,0
       0      .1       0     110     .05       0  195.62    .045       0
   207.8     .05       0  215.27      .1       0  333.37     .06       0
  433.37      .1       0
Bank Sta=195.62,207.8
XS Rating Curve= 0 ,0
Exp/Cntr(USF)=0,0
Exp/Cntr=0.3,0.1

Type RM Length L Ch R = 1 ,10895   ,203,208.4,212.5
XS GIS Cut Line= 4
  2272367.497556627322.9548259392272519.75780724 627478.25098458
2272575.73299431627468.9155143952272804.81465492627557.959808801
#Sta/Elev= 30
       0 2228.65    14.3 2227.01    18.1 2225.95    23.8 2222.86    31.1 2217.25
    38.8 2213.19    55.8 2206.78    69.5 2203.76   166.7 2202.06   211.4  2201.8
     226 2202.34   230.1 2202.15   232.7 2201.17     241 2196.39   246.6  2195.7
  254.74 2196.39   260.5 2199.19   270.6  2202.8   274.8 2203.58   291.9  2201.8
   300.5 2202.39   313.3 2204.53   361.3 2204.28   404.6 2206.33   426.2  2206.6
   437.8 2207.58   463.3 2212.73   494.2 2222.46   502.2 2223.77     520 2229.18
#Mann= 6 ,-1,0
       0      .1       0     180     .06       0     241    .045       0
  254.74     .06       0  294.23     .07       0  394.23     .06       0
Bank Sta=241,254.74
XS Rating Curve= 0 ,0
Exp/Cntr(USF)=0,0
Exp/Cntr=0.3,0.1

Type RM Length L Ch R = 1 ,10686   ,221,220,218.7
XS GIS Cut Line= 4
2272251.21662754627456.157299599 2272406.9003096627606.823400423
2272449.52638346627633.5691722582272631.45223009627702.673897224
#Sta/Elev= 30
       0 2218.67      13 2217.49    24.5 2214.99    29.2 2212.59    43.8 2202.93
    47.5 2201.17    52.3 2199.79    64.7 2198.78    76.2 2199.08    86.3 2198.19
     170 2197.75     185 2197.41   193.8  2196.4   222.2  2196.2   227.6 2194.48
   236.1 2190.38   243.7 2189.81  251.59 2190.41   260.7 2194.24   277.1 2197.58
   310.9 2196.18   325.4 2196.78   355.4 2199.24   367.3  2198.8   381.1 2199.78
   392.8 2199.78   436.2 2205.41   453.8 2209.57   458.1 2209.39   461.6  2210.4
#Mann= 8 ,-1,0
       0      .1       0      30     .06       0      60      .1       0
     170     .06       0     200     .05       0   236.1    .045       0
  251.59     .05       0  316.97     .06       0
Bank Sta=236.1,251.59
XS Rating Curve= 0 ,0
Exp/Cntr=0.3,0.1

Type RM Length L Ch R = 1 ,10466   ,82,86,89
XS GIS Cut Line= 4
2272174.96338357627544.0892077952272350.06554445627819.117964369
2272403.29416119627847.5393316292272642.86933339627886.545190272
#Sta/Elev= 30
       0 2214.38    39.2 2209.09    62.9 2202.47    76.7 2197.14    84.2 2195.83
     132 2193.25   186.2  2193.1   317.5 2190.11   328.4 2190.65     335 2189.13
  342.72 2185.17   346.9 2183.96   352.8 2185.15   361.6 2188.89   364.7 2189.15
   378.3  2187.5   387.3 2190.76   395.4 2191.66   403.5 2191.58   411.6 2190.31
   433.9 2189.73   468.3 2191.47     492 2193.82   504.8 2196.98   525.1  2203.4
   538.4 2205.89   553.4 2209.98   569.6 2211.74   577.7  2216.1   629.1 2231.04
#Mann= 8 ,-1,0
       0      .1       0      40     .06       0  342.72    .045       0
   352.8     .06       0  376.04     .07       0  476.38     .06       0
  516.38     .07       0  576.38      .1       0
#XS Ineff= 2 , 0
                          366.03         2194.32
Permanent Ineff=
       F       F
Bank Sta=342.72,352.8
XS Rating Curve= 0 ,0
Exp/Cntr(USF)=0,0
Exp/Cntr=0.3,0.1

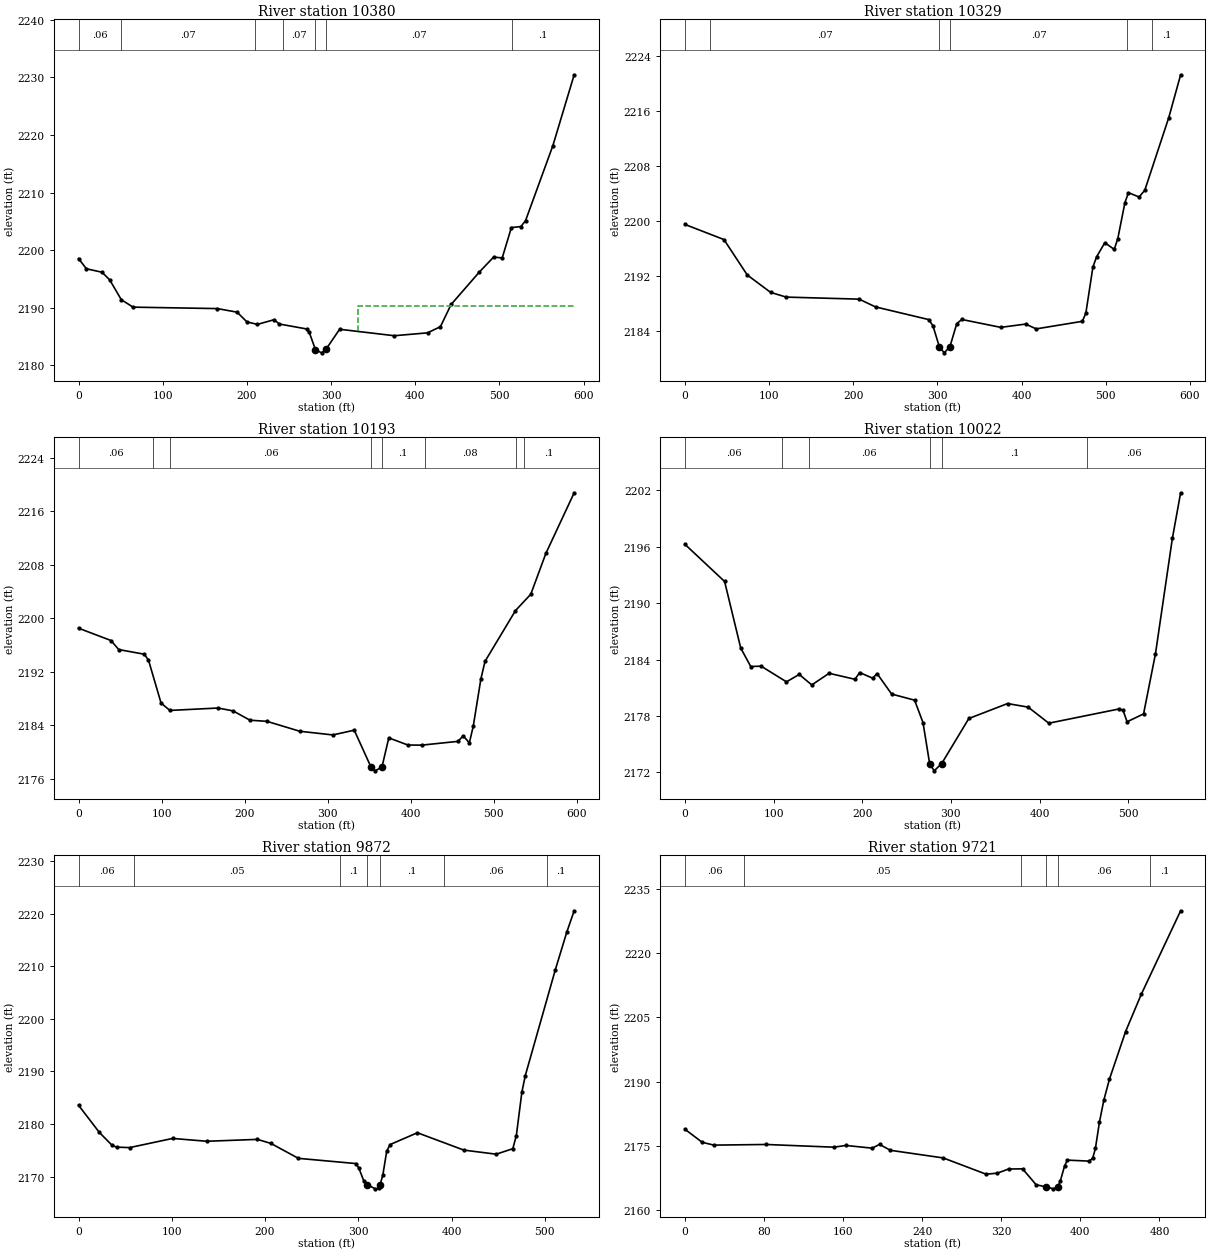
Type RM Length L Ch R = 1 ,10380   ,51.6,51,51.7
XS GIS Cut Line= 5
2272112.01540907 627743.943967062272313.29010818627860.072427492
2272360.71724379627951.3854716342272360.09520889627991.293870561
2272563.09040554628058.273018621
#Sta/Elev= 30
       0 2198.54     9.4 2196.77    27.9 2196.17    37.1 2194.84    50.8 2191.41
    64.8 2190.11     165 2189.86   188.4 2189.24   200.2 2187.54   212.6 2187.12
   232.4 2187.93   238.6 2187.18   270.9 2186.33   274.2 2185.72   281.52182.736
   288.7 2182.18   293.9 2182.76   310.2 2186.27   375.2 2185.15   414.7 2185.65
     430 2186.72   442.7 2190.57   476.4 2196.23   493.2  2198.8   503.4 2198.65
   514.3 2203.92   525.6  2204.1   531.1 2205.11   563.6 2218.14   588.9 2230.44
#Mann= 7 ,-1,0
       0     .06       0      50     .07       0     210     .06       0
  242.37     .07       0   281.5    .045       0   293.9     .07       0
  515.18      .1       0
#XS Ineff= 2 , 0
                           332.2         2190.39
Permanent Ineff=
       F       F
Bank Sta=281.5,293.9
XS Rating Curve= 0 ,0
Exp/Cntr(USF)=0,0
Exp/Cntr=0.3,0.1

Type RM Length L Ch R = 1 ,10329   ,134.7,136.5,138.3
XS GIS Cut Line= 5
2272076.05133476627769.7723313012272277.32603387627885.900791733
2272324.75316948627977.2138358752272324.13113458628017.122234802
2272527.12633123628084.101382862
#Sta/Elev= 30
       0 2199.49    46.3 2197.29      74 2192.13   101.7  2189.6   120.2 2188.91
   206.9 2188.61   226.4 2187.48   289.7 2185.63   294.7  2184.7   302.2 2181.68
     308 2180.79  314.78 2181.68   322.9 2185.04   328.9 2185.65   375.2  2184.5
   404.7 2184.98   417.3 2184.28   472.1 2185.38   476.3 2186.58   484.7  2193.3
     489 2194.76   498.8 2196.83     510 2195.86   514.2  2197.4   522.7 2202.66
   526.9 2204.12   539.5 2203.49   546.3 2204.47   574.8 2215.05   588.9 2221.29
#Mann= 6 ,-1,0
       0     .06       0      30     .07       0   302.2    .045       0
  314.78     .07       0  525.18     .06       0  555.18      .1       0
Bank Sta=302.2,314.78
XS Rating Curve= 0 ,0
Exp/Cntr(USF)=0,0
Exp/Cntr=0.3,0.1

Type RM Length L Ch R = 1 ,10193   ,174.4,170.6,160.7
XS GIS Cut Line= 4
2272043.88742642627783.2699102532272244.40956698628036.539306438
2272258.96275913628088.2472934652272449.34534107628198.606785126
#Sta/Elev= 30
       0 2198.52    39.1 2196.68    48.4 2195.33      79 2194.64    84.2 2193.78
    99.4 2187.34     110 2186.24     168  2186.6   186.1 2186.17   206.5 2184.78
   226.9 2184.61   266.4 2183.13   306.2 2182.58     332 2183.29   352.22177.772
   356.9 2177.22   365.3 2177.76   373.6 2182.14   396.7 2181.07   413.4 2181.06
   456.8 2181.62   463.2 2182.44   470.6  2181.4   475.3 2183.88   484.5 2190.96
   489.5 2193.58   526.1 2201.14   544.6  2203.6   562.7 2209.68   596.8 2218.74
#Mann= 8 ,-1,0
       0     .06       0      90     .07       0     110     .06       0
   352.2    .045       0   365.3      .1       0  416.76     .08       0
  526.76     .06       0  536.76      .1       0
Bank Sta=352.2,365.3
XS Rating Curve= 0 ,0
Exp/Cntr(USF)=0,0
Exp/Cntr=0.3,0.1

Type RM Length L Ch R = 1 ,10022   ,151.9,149.9,144.5
XS GIS Cut Line= 4
2271920.80400928627876.7823418222272065.05591333628079.053434397
2272146.36228547628105.3932710092272340.13534509628220.105283738
#Sta/Elev= 30
       0 2196.26    44.7 2192.31    62.9 2185.22    74.2 2183.26    85.9  2183.3
   114.5 2181.63   128.9 2182.42     143  2181.3   162.6 2182.54   191.8  2181.9
     197 2182.62   211.7 2182.02   216.7 2182.51   233.1 2180.33     259 2179.68
   268.5 2177.29  275.98 2172.93   281.1 2172.16   289.6 2172.94   320.2 2177.73
   363.9 2179.32   387.1 2178.94   410.4 2177.23   489.4 2178.74   494.1 2178.61
   498.7 2177.38   517.3 2178.22   530.7 2184.61   549.8 2196.91   559.1 2201.75
#Mann= 6 ,-1,0
       0     .06       0     110     .05       0     140     .06       0
  275.98    .045       0   289.6      .1       0  453.91     .06       0
Bank Sta=275.98,289.6
XS Rating Curve= 0 ,0
Exp/Cntr(USF)=0,0
Exp/Cntr=0.3,0.1

Type RM Length L Ch R = 1 ,9872    ,145.2,150.9,156.4
XS GIS Cut Line= 4
2271852.69170917628091.0399253272272104.33876571628234.513233192
2272175.07124118628218.7585311042272327.21933977 628293.05060027
#Sta/Elev= 30
       0 2183.58    22.4 2178.39    36.2 2175.92    40.8 2175.61    54.7 2175.51
   100.9 2177.26   137.5 2176.72   191.8 2177.08   206.2 2176.32   235.8 2173.47
   297.4 2172.48   300.7 2171.57   305.9 2169.19   309.82168.458   318.2 2167.67
   322.3 2167.74  323.46 2168.48   326.4 2170.37   330.5 2174.85   334.2  2176.1
   363.4 2178.34   413.2 2175.04   447.9 2174.26   465.7 2175.31   469.5 2177.81
   475.4 2186.04   479.1 2189.22   511.3 2209.35   523.6 2216.52   531.5 2220.57
#Mann= 7 ,-1,0
       0     .06       0      60     .05       0     280      .1       0
   309.8    .045       0  323.46      .1       0  392.14     .06       0
  502.14      .1       0
Bank Sta=309.8,323.46
XS Rating Curve= 0 ,0
Exp/Cntr(USF)=0,0
Exp/Cntr=0.3,0.1

Type RM Length L Ch R = 1 ,9721    ,191.7,187.9,184.8
XS GIS Cut Line= 2
2271837.98202968628129.8404208732272218.45095553628456.381332202
#Sta/Elev= 30
       0 2178.89    17.4 2175.85    29.2 2175.19      82 2175.34   150.5 2174.71
   162.8 2175.11   189.4 2174.48   196.8 2175.36   207.8 2173.98   261.2  2172.2
   304.6  2168.4     316 2168.64   327.3 2169.61   341.5 2169.65   355.2 2165.94
   365.62165.422   372.7 2164.98   377.1 2165.44   379.8  2166.9     384 2170.32
   386.9 2171.69   408.8 2171.45   412.4 2172.11   415.2 2174.43   419.3 2180.61
   423.7 2185.68   429.4 2190.61   445.7  2201.7   461.5 2210.37   501.4 2229.92
#Mann= 6 ,-1,0
       0     .06       0      60     .05       0     340     .06       0
   365.6    .045       0   377.1     .06       0     470      .1       0
Bank Sta=365.6,377.1
XS Rating Curve= 0 ,0
Exp/Cntr(USF)=0,0
Exp/Cntr=0.3,0.1

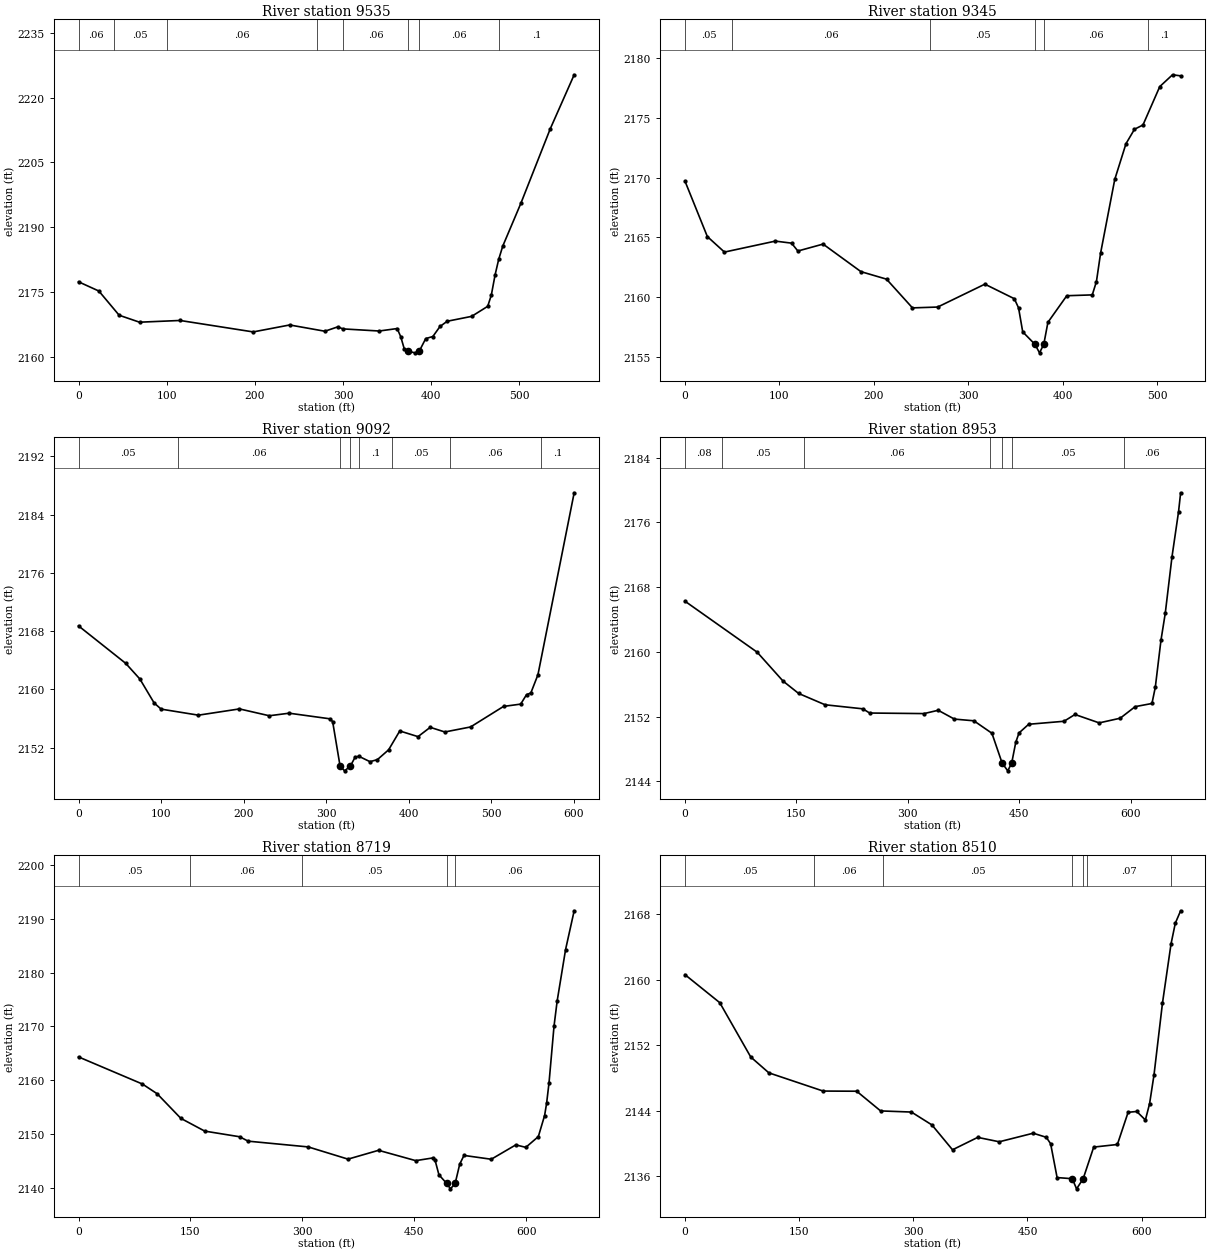
Type RM Length L Ch R = 1 ,9535    ,187,192.7,197.1
XS GIS Cut Line= 4
2271668.12454869628311.9207932522271965.59507431628481.911622672
2272039.14594686 628494.448703222272178.15782972628535.944992652
#Sta/Elev= 30
       0 2177.36    23.1 2175.22    46.1 2169.62    69.2 2168.01   115.2 2168.41
   198.2 2165.76   239.6 2167.37   279.5 2165.92   294.1 2166.93     300 2166.46
   341.1 2165.97   361.5 2166.54   365.5 2164.68   369.6 2161.81   373.6  2161.3
   381.8 2160.92  386.52 2161.29   393.9 2164.22     402  2164.7   410.1 2167.02
   418.3 2168.23     446 2169.36   464.2 2171.68   468.3 2174.26   472.6 2178.97
   476.7 2182.57   481.3 2185.62   501.8  2195.5   535.2 2212.77   562.3 2225.26
#Mann= 8 ,-1,0
       0     .06       0      40     .05       0     100     .06       0
     270     .05       0     300     .06       0   373.6    .045       0
  386.52     .06       0  477.23      .1       0
Bank Sta=373.6,386.52
XS Rating Curve= 0 ,0
Exp/Cntr=0.3,0.1

Type RM Length L Ch R = 1 ,9345    ,256.7,253.1,248.7
XS GIS Cut Line= 4
2271595.18336556628436.6502390692271875.02238606628583.806965369
2271907.89041297628650.7436475052272027.85759707628711.192173166
#Sta/Elev= 30
       0 2169.71    23.7 2165.06    41.8 2163.76    95.7 2164.68   112.9 2164.51
   119.6 2163.85   146.3 2164.43   186.4 2162.12   213.5 2161.49     241 2159.08
   267.7 2159.15   317.7 2161.07   348.9 2159.85   353.4 2159.08   357.8 2157.07
  370.78 2156.02   375.6 2155.31   380.1 2156.02   384.5 2157.87   404.5  2160.1
   431.5 2160.17   435.9 2161.29   440.3 2163.67   455.3 2169.85   467.2 2172.85
   476.2 2174.06   485.2 2174.42     503 2177.64   516.5 2178.63   525.1 2178.54
#Mann= 6 ,-1,0
       0     .05       0      50     .06       0     260     .05       0
  370.78    .045       0   380.1     .06       0  490.74      .1       0
Bank Sta=370.78,380.1
XS Rating Curve= 0 ,0
Exp/Cntr(USF)=0,0
Exp/Cntr=0.3,0.1

Type RM Length L Ch R = 1 ,9092    ,139.6,139.5,138.8
XS GIS Cut Line= 2
2271403.50692968628578.6153955522271935.24727973628857.572352466
#Sta/Elev= 30
       0 2168.72    57.2 2163.57    74.4 2161.41    91.6 2158.13   100.1 2157.28
   145.3 2156.45     195 2157.31   231.1 2156.37   255.2 2156.72   304.6 2155.95
   307.9 2155.56   316.9 2149.45   322.4  2148.8   329.3 2149.44     335 2150.66
   339.5 2150.81   353.1 2150.06   362.1 2150.34   375.7 2151.69   389.2 2154.28
   411.3  2153.5   426.1 2154.78   443.8 2154.14     475 2154.83   514.9 2157.65
   535.7 2157.97   542.8 2159.27     548  2159.5   556.6    2162   600.5 2187.01
#Mann= 8 ,-1,0
       0     .05       0     120     .06       0   316.9    .045       0
   329.3     .06       0     340      .1       0     380     .05       0
     450     .06       0     560      .1       0
Bank Sta=316.9,329.3
XS Rating Curve= 0 ,0
Exp/Cntr(USF)=0,0
Exp/Cntr=0.3,0.1

Type RM Length L Ch R = 1 ,8953    ,234,234.6,236.8
XS GIS Cut Line= 3
2271266.78885807628692.316748641 2271717.9949196 628885.23431064
2271874.39360754628966.721150159
#Sta/Elev= 30
       0 2166.26    97.2 2159.95     132 2156.38     153 2154.85   188.6 2153.45
   239.4 2152.95   248.5 2152.43   321.7 2152.36   340.8 2152.77   362.6 2151.68
   388.8 2151.47   413.1 2149.93   426.82146.253   434.4 2145.28   439.7 2146.23
   445.2 2148.81   449.6 2149.97   462.6 2151.04   510.1 2151.41   524.9 2152.25
   557.5 2151.21   585.8 2151.79   605.9 2153.22   628.5 2153.61     633 2155.61
   640.6 2161.41   646.4 2164.76   655.5 2171.77   664.3 2177.33   667.1 2179.67
#Mann= 7 ,-1,0
       0     .08       0      50     .05       0     160     .06       0
     410     .05       0   426.8    .045       0   439.7     .05       0
  590.72     .06       0
Bank Sta=426.8,439.7
XS Rating Curve= 0 ,0
Exp/Cntr(USF)=0,0
Exp/Cntr=0.3,0.1

Type RM Length L Ch R = 1 ,8719    ,207.4,208.3,209.2
XS GIS Cut Line= 4
2271233.32263303628755.2526319842271573.30475188629055.094775409
2271625.17148684629097.6799513642271761.79650414629142.032290159
#Sta/Elev= 30
       0 2164.34    85.6  2159.3   105.4 2157.49   137.1 2152.92   169.1 2150.55
   215.9  2149.5   227.3 2148.68   307.8 2147.61   361.1 2145.34     402 2146.98
   451.8 2145.06   475.5 2145.58   477.7 2145.16   482.9 2142.43   493.3 2140.82
   498.4 2139.82  504.64 2140.82   510.8 2144.43   516.5 2146.03     553 2145.32
   585.9 2147.99   599.3 2147.53   616.1 2149.53   624.5 2153.45   627.2 2155.75
   630.4 2159.51   637.1 2170.05   641.3 2174.72   652.6  2184.3   664.1  2191.5
#Mann= 5 ,-1,0
       0     .05       0     150     .06       0     300     .05       0
   493.3    .045       0  504.64     .06       0
Bank Sta=493.3,504.64
XS Rating Curve= 0 ,0
Exp/Cntr(USF)=0,0
Exp/Cntr=0.3,0.1

Type RM Length L Ch R = 1 ,8510    ,144.3,145.4,145.7
XS GIS Cut Line= 3
2271232.41806004628820.5495958592271414.39854576629174.790359242
2271592.78466213629354.094078609
#Sta/Elev= 30
       0 2160.63    45.7  2157.2    86.4 2150.55   110.2 2148.61   181.5 2146.38
   225.6 2146.36     257 2143.95   297.5 2143.81   324.5 2142.23   351.5 2139.19
   384.6 2140.71   412.9 2140.17   457.5 2141.22   474.7 2140.72   480.4 2139.93
   488.9 2135.79   508.8 2135.65   514.5 2134.41   523.12135.635     537 2139.52
   568.1 2139.84   582.2 2143.78   593.5 2143.88   604.9 2142.84   610.4 2144.83
   616.2 2148.35   627.3 2157.12   638.6  2164.4   644.2 2166.93   651.2 2168.45
#Mann= 7 ,-1,0
       0     .05       0     170     .06       0     260     .05       0
   508.8    .045       0   523.1     .05       0  528.25     .07       0
  638.25     .06       0
Bank Sta=508.8,523.1
XS Rating Curve= 0 ,0
Exp/Cntr=0.3,0.1