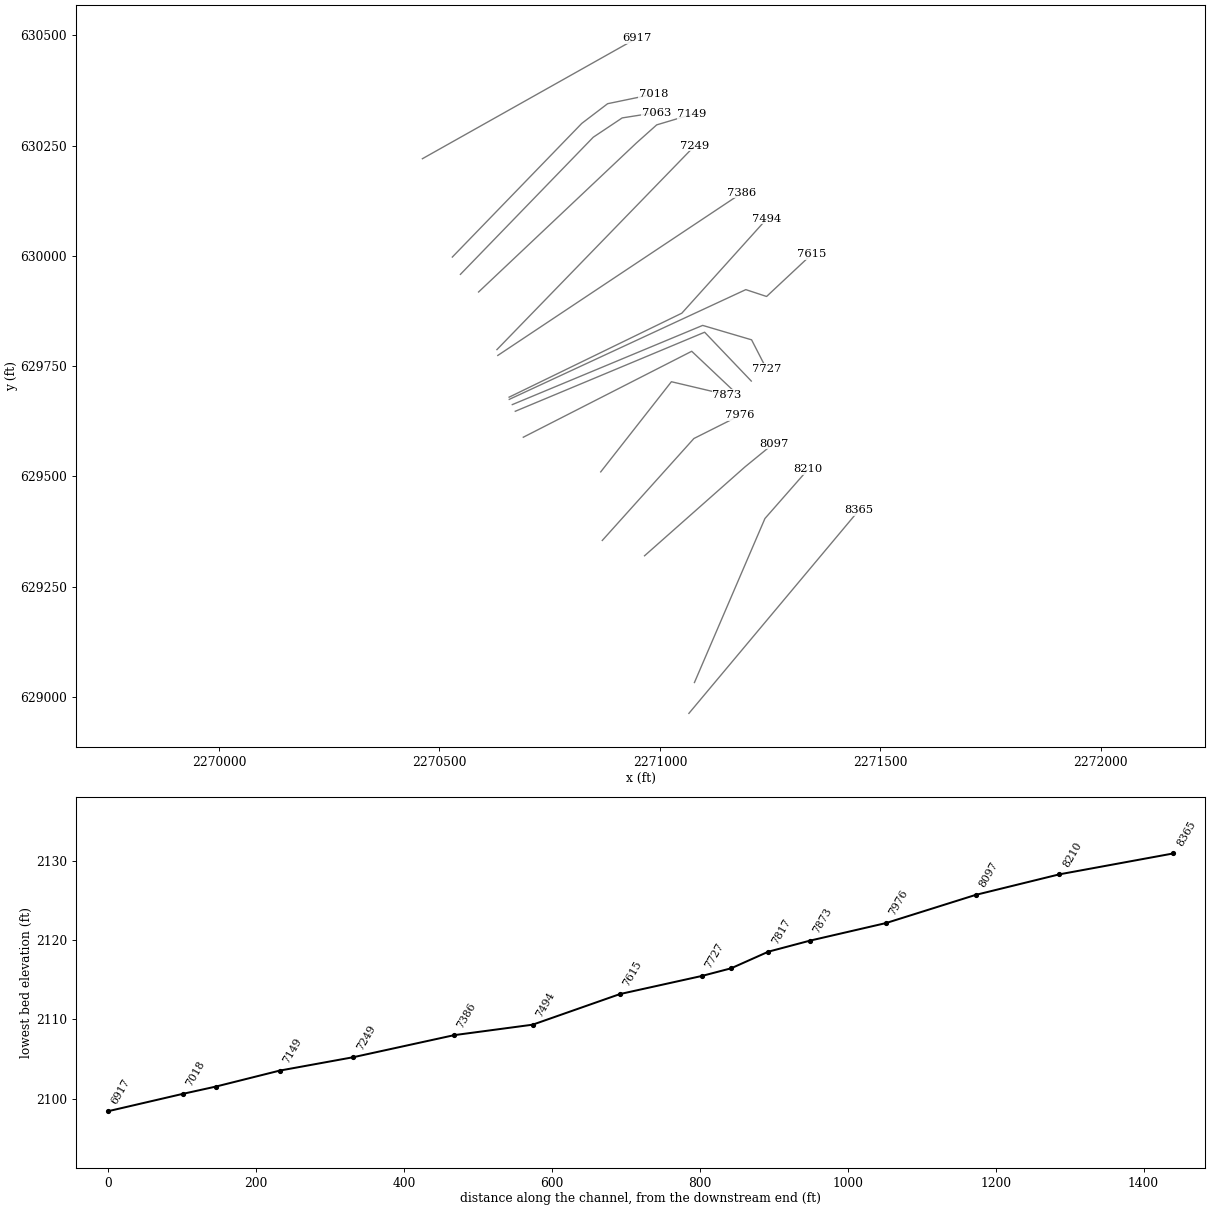
HEC-RAS study DRYRN.prj: DRYRN

--- DRYRN.g01 (geometry) --- (continued)

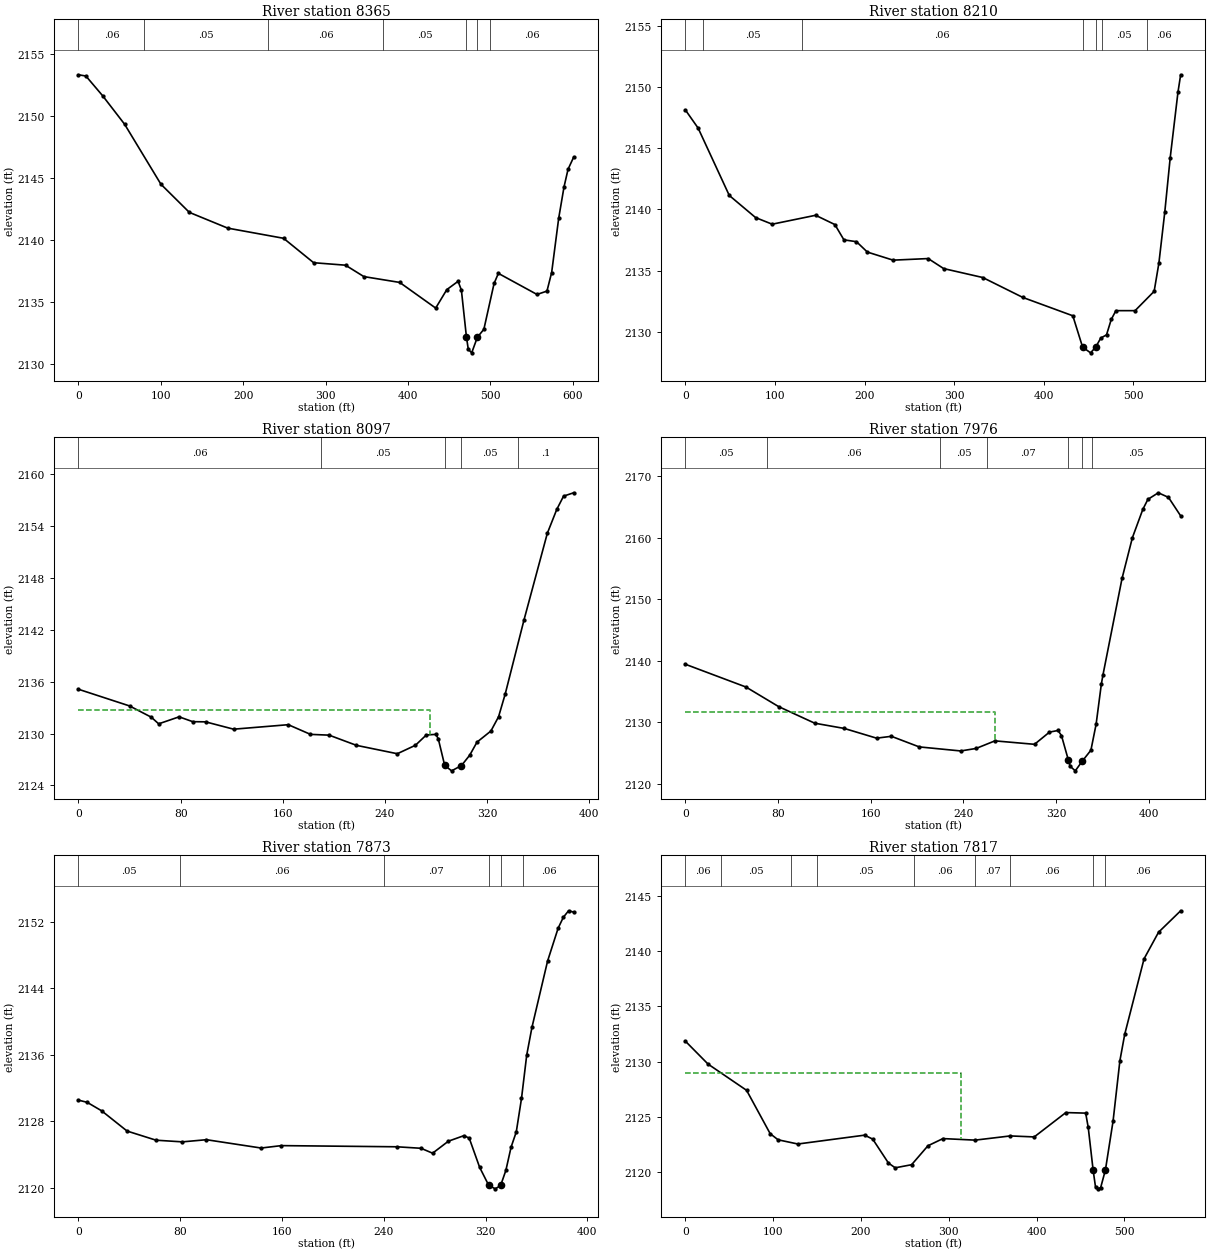
Type RM Length L Ch R = 1 ,8365    ,153.7,154.3,153.4
XS GIS Cut Line= 2
2271065.76514127628962.2620981682271451.67101123629423.278245416
#Sta/Elev= 30
       0 2153.34       9 2153.24    29.3 2151.65      56 2149.35   100.1 2144.51
   134.6 2142.24   181.2 2140.97     249 2140.15   285.5 2138.18   324.2 2137.98
   346.5 2137.06     390 2136.59   433.7 2134.52   447.2 2136.01   460.9 2136.68
   464.9 2135.97  471.04 2132.18   473.3 2131.19   477.4 2130.91   484.32132.167
   492.2 2132.81   504.6 2136.51   509.8 2137.32   556.7 2135.62   568.8 2135.89
   574.5 2137.39     583 2141.75   589.5 2144.29   594.4 2145.72   601.2 2146.69
#Mann= 7 ,-1,0
       0     .06       0      80     .05       0     230     .06       0
     370     .05       0  471.04    .045       0   484.3     .05       0
     500     .06       0
Bank Sta=471.04,484.3
XS Rating Curve= 0 ,0
Exp/Cntr(USF)=0,0
Exp/Cntr=0.3,0.1

Type RM Length L Ch R = 1 ,8210    ,113.8,113.1,112.1
XS GIS Cut Line= 3
2271078.32165875629032.225600455 2271238.2107413629404.210081355
2271335.84877669 629515.41406891
#Sta/Elev= 30
       0 2148.12    14.1 2146.65    48.9 2141.14    78.3 2139.33    96.8 2138.79
   145.3 2139.52   166.8 2138.76   176.9 2137.51   190.9 2137.36   203.1 2136.51
   231.8 2135.85     271 2135.98   288.3 2135.16   331.9 2134.43   376.7  2132.8
   432.5  2131.3   443.4 2128.74   452.3 2128.27  457.98 2128.73   463.7 2129.48
   470.1 2129.74   475.4    2131   480.6 2131.72     502 2131.72   523.3  2133.3
   528.6 2135.61   535.2  2139.8   541.2 2144.21   549.9 2149.59   552.9 2151.01
#Mann= 7 ,-1,0
       0     .06       0      20     .05       0     130     .06       0
   443.4    .045       0  457.98     .06       0  464.89     .05       0
  514.89     .06       0
Bank Sta=443.4,457.98
XS Rating Curve= 0 ,0
Exp/Cntr(USF)=0,0
Exp/Cntr=0.3,0.1

Type RM Length L Ch R = 1 ,8097    ,122.8,121.2,119.9
XS GIS Cut Line= 3
2270965.17477068629319.6956269582271192.80728193629521.159349312
2271257.70122707629574.182450824
#Sta/Elev= 30
       0 2135.12      40 2133.19      57 2131.89    62.8 2131.12    78.8 2131.93
    89.5 2131.37    99.5 2131.35   121.5  2130.5   164.3 2131.02   181.7  2129.9
   196.3 2129.81   217.7 2128.63   249.7 2127.66   263.9 2128.64   272.4 2129.83
   279.9  2129.9   281.8 2129.38   286.8 2126.31   292.2 2125.68  299.94 2126.29
   306.4 2127.49   312.1    2129     323 2130.29     329 2131.94   334.2 2134.57
     349 2143.19   367.2 2153.18   374.6 2155.94   379.9 2157.47   387.8 2157.86
#Mann= 5 ,-1,0
       0     .06       0     190     .05       0   286.8    .045       0
  299.94     .05       0  343.98      .1       0
#XS Ineff= 2 , 0
          274.96 2132.69
Permanent Ineff=
       T       F
Bank Sta=286.8,299.94
XS Rating Curve= 0 ,0
Exp/Cntr=0.3,0.1

Type RM Length L Ch R = 1 ,7976    ,106.7,103.4,99.3
XS GIS Cut Line= 3
2270869.31802524629354.4449432182271077.06513422629585.638658748
2271181.40441515629637.995589722
#Sta/Elev= 30
       0 2139.44    52.2 2135.75    80.4 2132.57   111.6 2129.87   137.1 2129.02
     165 2127.44   177.8 2127.74   201.8 2126.02   237.7 2125.36     251 2125.77
   267.2    2127   301.4 2126.44   314.3 2128.42   321.7 2128.69   324.7 2127.85
   330.7 2123.83   332.2 2122.87   336.6 2122.13   342.6  2123.7   350.1 2125.48
   354.6 2129.71   359.1 2136.21   360.5 2137.71     377 2153.41   385.9    2160
   394.9  2164.6   399.3 2166.24   408.3 2167.31   417.1 2166.56   427.6 2163.56
#Mann= 7 ,-1,0
       0     .05       0      70     .06       0     220     .05       0
     260     .07       0   330.7    .045       0   342.6     .07       0
  350.82     .05       0
#XS Ineff= 2 , 0
           267.1 2131.62
Permanent Ineff=
       T       F
Bank Sta=330.7,342.6
XS Rating Curve= 0 ,0
Exp/Cntr(USF)=0,0
Exp/Cntr=0.3,0.1

Type RM Length L Ch R = 1 ,7873    ,60.6,55.7,53.3
XS GIS Cut Line= 3
2270865.77666565629509.9686078222271026.06244432629714.444788497
2271152.09369016629684.675633229
#Sta/Elev= 30
       0 2130.55     6.8 2130.29    18.2 2129.27    38.2 2126.84      61 2125.74
    81.7 2125.54   100.6  2125.8   143.6  2124.8   159.5 2125.09   250.3 2124.95
   269.3 2124.77   278.4 2124.18   290.8 2125.62   303.1 2126.29   307.2 2125.99
   315.4 2122.48   322.5 2120.33   327.7  2119.9   331.9 2120.31     336 2122.11
   340.1  2124.9   344.2 2126.74   348.3 2130.75   352.4 2135.96   356.5 2139.28
   368.8 2147.25   377.1  2151.2   381.2 2152.51   385.3 2153.29   389.3 2153.13
#Mann= 6 ,-1,0
       0     .05       0      80     .06       0     240     .07       0
   322.5    .045       0   331.9     .07       0  349.81     .06       0
Bank Sta=322.5,331.9
XS Rating Curve= 0 ,0
Exp/Cntr(USF)=0,0
Exp/Cntr=0.3,0.1

Type RM Length L Ch R = 1 ,7817    ,49.8,50.2,49.6
XS GIS Cut Line= 3
2270690.19914296629588.5846979082271072.13606827629783.502809301
2271170.48125622629690.621242908
#Sta/Elev= 30
       0 2131.85    25.7 2129.79    69.6 2127.42    96.5  2123.5   105.5 2122.95
     128 2122.57   204.1 2123.37   213.3 2123.01   231.2 2120.85   238.9 2120.42
   257.6  2120.7   276.2 2122.41   293.3 2123.06     330 2122.92     370  2123.3
   397.3 2123.21   433.3 2125.41   455.9 2125.36   458.8 2124.07   464.4  2120.2
   467.1 2118.69   470.1 2118.52     473 2118.64   478.4 2120.23   487.1 2124.64
   494.9 2130.11   500.4 2132.49   522.4  2139.3   538.9  2141.7   564.1 2143.64
#Mann= 9 ,-1,0
       0     .06       0      40     .05       0     120     .06       0
     150     .05       0     260     .06       0     330     .07       0
     370     .06       0   464.4    .045       0   478.4     .06       0
#XS Ineff= 2 , 0
           313.4 2129.02
Permanent Ineff=
       F       F
Bank Sta=464.4,478.4
XS Rating Curve= 0 ,0
Exp/Cntr(USF)=0,0
Exp/Cntr=0.3,0.1

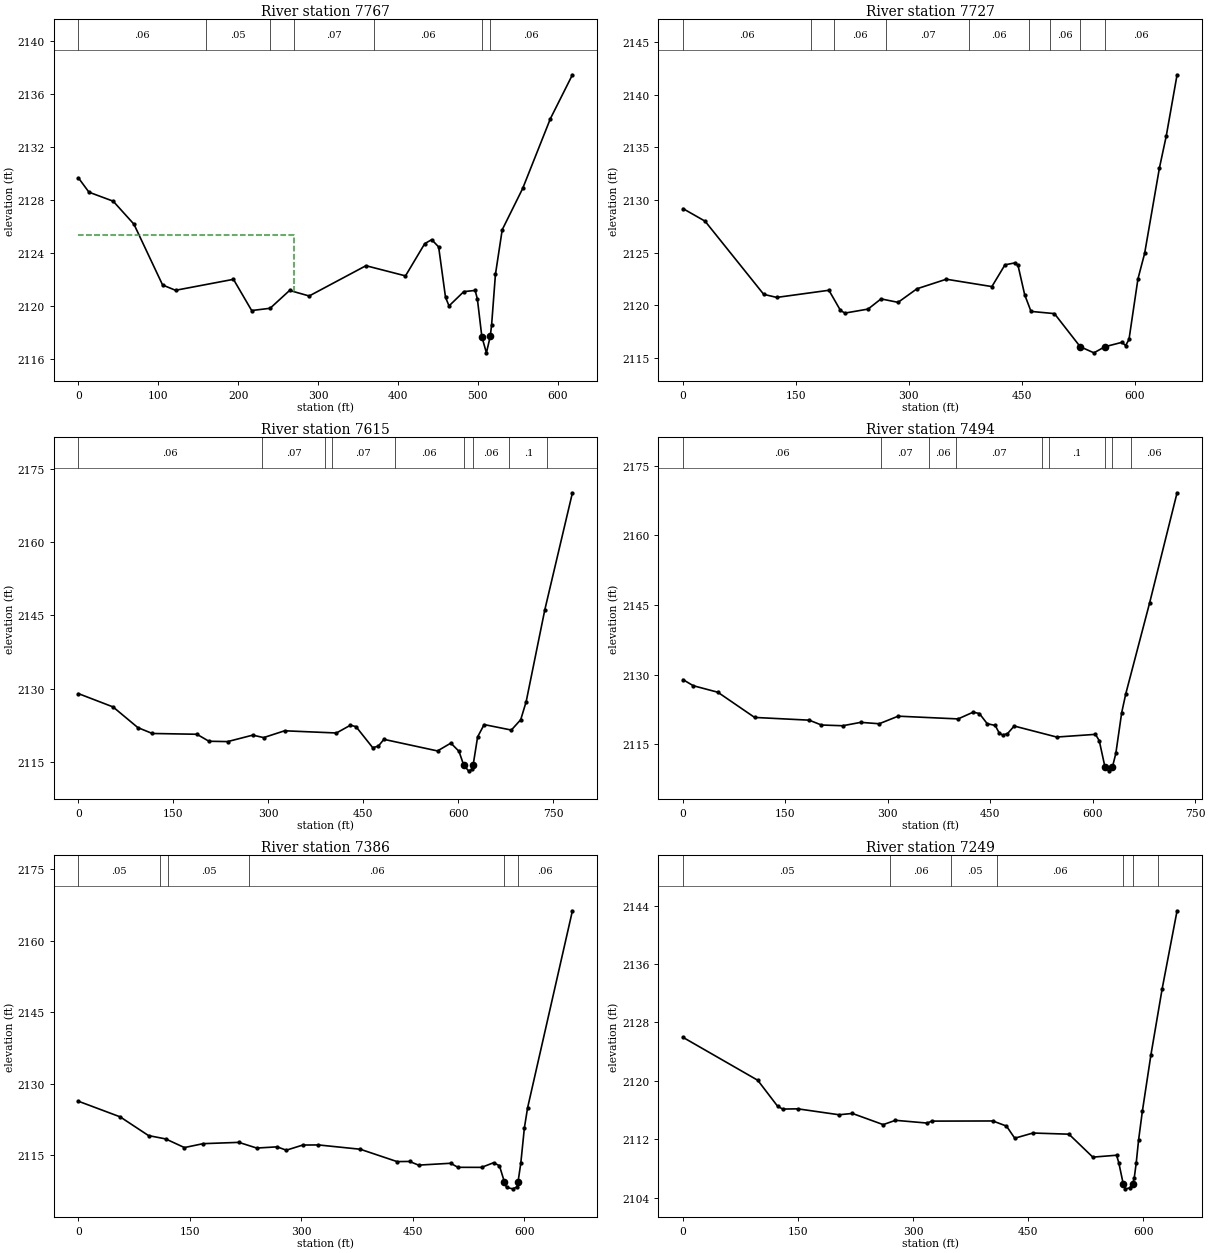
Type RM Length L Ch R = 1 ,7767    ,37.5,39.3,56.4
XS GIS Cut Line= 3
 2270672.0042794629647.4375695052271101.44094751629826.715088853
2271207.23652848629715.952579197
#Sta/Elev= 30
       0 2129.66    13.2 2128.58    43.5  2127.9    69.5 2126.16   105.4 2121.56
   121.6 2121.16   194.1 2121.99   216.9 2119.63     240  2119.8   264.4 2121.15
   288.9 2120.73     360 2123.02   409.5 2122.25   433.6 2124.69   442.3 2124.99
     451 2124.44   459.6 2120.63     464 2119.98   482.5 2121.06   496.7 2121.15
   499.5  2120.5   505.12117.646   510.8 2116.43   515.62117.671   517.3 2118.53
   522.1 2122.36   530.6 2125.74   556.2 2128.86   590.9 2134.14   618.5 2137.46
#Mann= 7 ,-1,0
       0     .06       0     160     .05       0     240     .06       0
     270     .07       0     370     .06       0   505.1    .045       0
   515.6     .06       0
#XS Ineff= 2 , 0
          269.87 2125.33
Permanent Ineff=
       T       F
Bank Sta=505.1,515.6
XS Rating Curve= 0 ,0
Exp/Cntr(USF)=0,0
Exp/Cntr=0.3,0.1

Type RM Length L Ch R = 1 ,7727    ,109.8,111.1,105.8
XS GIS Cut Line= 4
2270665.24485025629662.5399973032271096.97312631629842.188983838
2271207.93593954 629809.470036022271241.39484363629744.326838094
#Sta/Elev= 30
       0 2129.18    29.2 2127.99   107.2 2121.03   124.5 2120.74   193.8 2121.42
   209.2  2119.5   215.1 2119.25   245.8 2119.63   263.1  2120.6   285.7 2120.27
   310.8 2121.56   349.8 2122.47   410.4 2121.77   427.8 2123.84   440.8 2124.02
   445.1 2123.79     454 2120.99   462.4 2119.41   493.5  2119.2   527.8 2116.05
     546 2115.47  560.54 2116.05   583.3 2116.47   588.1 2116.16   592.6 2116.74
   604.5  2122.5   613.4 2124.93   633.1 2133.07   642.1 2136.08   656.5 2141.91
#Mann= 9 ,-1,0
       0     .06       0     170     .05       0     200     .06       0
     270     .07       0     380     .06       0     460     .07       0
  487.61     .06       0   527.8    .045       0  560.54     .06       0
Bank Sta=527.8,560.54
XS Rating Curve= 0 ,0
Exp/Cntr(USF)=0,0
Exp/Cntr=0.3,0.1

Type RM Length L Ch R = 1 ,7615    ,109.2,118,124.7
XS GIS Cut Line= 4
2270658.31989618629674.3911345122271194.86106374629923.328300795
2271241.93469731629907.7687018042271343.86173873630003.125393873
#Sta/Elev= 30
       0 2128.97    54.7 2126.25    93.9 2122.02   116.7 2120.82   187.2 2120.66
   206.2 2119.23   235.8 2119.16   275.4 2120.48   292.7 2119.98   325.8 2121.37
   407.7 2120.92   429.8 2122.51   438.6 2122.22     465 2117.92   473.9 2118.23
   482.7 2119.62   567.4 2117.25   588.5 2118.85   601.3 2117.18   608.82114.355
   616.4 2113.18   622.4 2113.47   623.62114.283   630.8 2120.13   641.1 2122.64
   684.1 2121.52   698.9 2123.64   707.5 2127.33     737 2146.13   780.6 2170.04
#Mann= 9 ,-1,0
       0     .06       0     290     .07       0     390     .06       0
     400     .07       0     500     .06       0   608.8    .045       0
   623.6     .06       0  681.06      .1       0  741.06     .06       0
Bank Sta=608.8,623.6
XS Rating Curve= 0 ,0
Exp/Cntr(USF)=0,0
Exp/Cntr=0.3,0.1

Type RM Length L Ch R = 1 ,7494    ,106.5,106.2,104
XS GIS Cut Line= 3
2270657.94479012629679.3956621462271049.76699972 629869.91468385
2271242.44893683630083.905104061
#Sta/Elev= 30
       0 2128.93      15 2127.63    50.9 2126.23   104.8 2120.81   184.8 2120.22
   202.6 2119.18   233.8 2119.02   260.2 2119.75   287.3 2119.45   315.1 2121.08
   402.8 2120.49   424.9 2121.94     434 2121.65   445.5 2119.46   457.2 2119.09
   463.2 2117.43     468 2117.04   475.2 2117.32     485 2118.96   547.3 2116.59
     604 2117.17   609.6 2115.82   618.1 2110.06   623.8 2109.32  628.78 2110.06
   633.9 2113.07   642.5 2121.86   648.5 2125.91   683.3  2145.4   723.6 2169.14
#Mann= 9 ,-1,0
       0     .06       0     290     .07       0     360     .06       0
     400     .07       0  525.69     .06       0  535.69      .1       0
   618.1    .045       0  628.78      .1       0  655.69     .06       0
Bank Sta=618.1,628.78
XS Rating Curve= 0 ,0
Exp/Cntr(USF)=0,0
Exp/Cntr=0.3,0.1

Type RM Length L Ch R = 1 ,7386    ,134.8,136.3,137.7
XS GIS Cut Line= 2
 2270632.3730398629774.0772024522271186.05383666630142.663430845
#Sta/Elev= 30
       0 2126.36    56.1 2123.09    94.4 2119.16   117.5 2118.46   142.7 2116.65
   167.9 2117.47     216 2117.74     240 2116.55   267.5  2116.8   279.9  2116.1
   302.1 2117.18   323.2  2117.2   379.4  2116.3     429 2113.71   445.9 2113.74
   457.9 2112.97   501.2 2113.36   510.9 2112.51   542.8  2112.5   558.9 2113.47
   566.8 2112.85   573.6 2109.41   576.4 2108.29   584.8    2108   590.3 2108.38
   591.8 2109.37   595.6 2113.39   600.4 2120.76   604.7 2124.95   665.1 2166.28
#Mann= 6 ,-1,0
       0     .05       0     110     .06       0     120     .05       0
     230     .06       0   573.6    .045       0   591.8     .06       0
Bank Sta=573.6,591.8
XS Rating Curve= 0 ,0
Exp/Cntr(USF)=0,0
Exp/Cntr=0.3,0.1

Type RM Length L Ch R = 1 ,7249    ,99.6,99.6,98.8
XS GIS Cut Line= 2
2270630.39205088629787.286426741 2271079.0843163630249.632951203
#Sta/Elev= 30
       0 2125.95    97.4 2120.08   123.2 2116.54   129.9 2116.14   149.7 2116.17
   203.4 2115.36   220.8 2115.54     261 2114.01     277  2114.6   318.5 2114.22
   324.2 2114.49     404 2114.51   421.8 2113.81   432.6 2112.15   456.3 2112.86
   503.3  2112.7   534.4 2109.56   565.4 2109.82   568.3 2108.79     574 2105.94
   576.8 2105.22   582.5 2105.34  586.26 2105.93   588.4 2106.67     591 2108.74
   594.1  2111.9     599 2115.82   610.2 2123.56   624.9 2132.63   644.3 2143.28
#Mann= 7 ,-1,0
       0     .05       0     270     .06       0     350     .05       0
     410     .06       0     574    .045       0  586.26     .06       0
     620      .1       0
Bank Sta=574,586.26
XS Rating Curve= 0 ,0
Exp/Cntr(USF)=0,0
Exp/Cntr=0.3,0.1

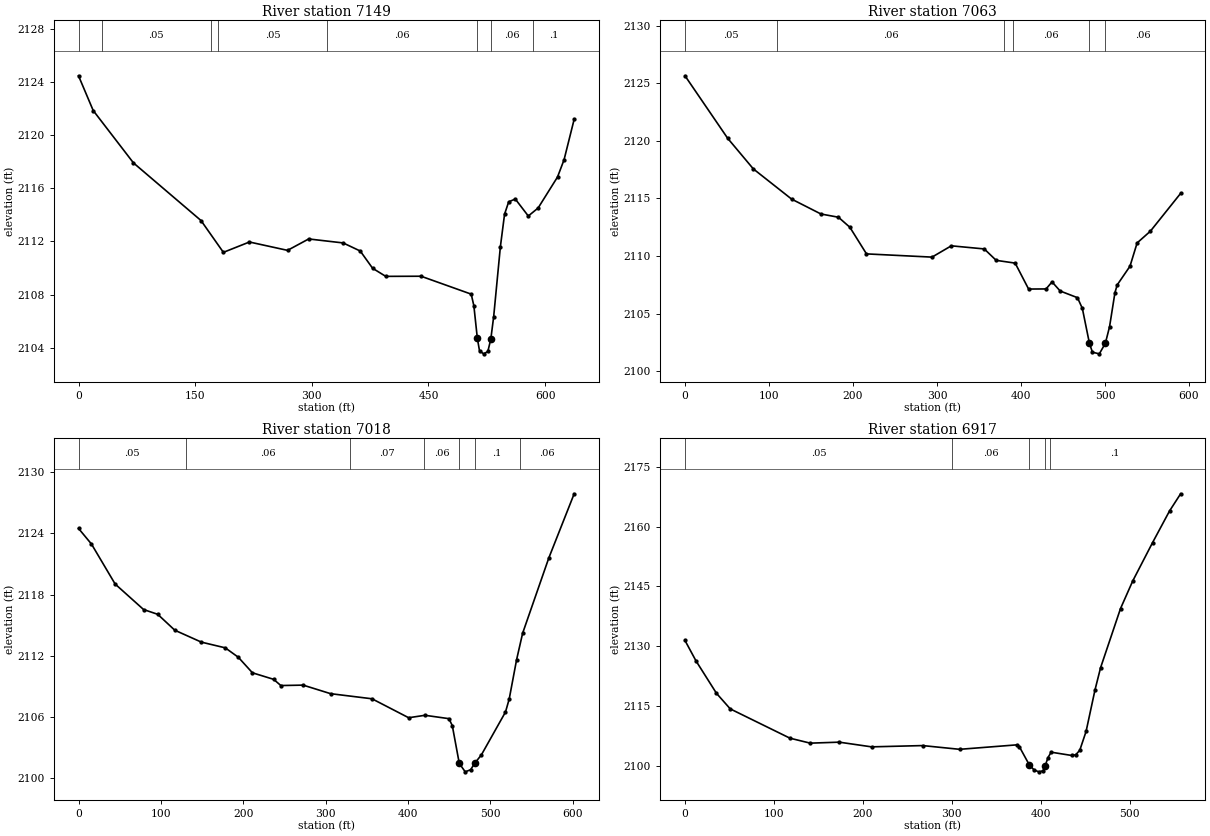
Type RM Length L Ch R = 1 ,7149    ,84.5,86.1,80.4
XS GIS Cut Line= 4
2270588.74994487629917.955011267 2270946.6945223630255.915218186
2270992.73379319  630296.9757372  2271072.695321630320.860349401
#Sta/Elev= 30
       0 2124.49    18.9 2121.87    70.7 2117.92   157.5 2113.58   186.3 2111.18
   219.8 2111.96   268.8 2111.33     296 2112.19   340.3 2111.89   362.3 2111.28
   378.2 2109.98   395.1 2109.37   440.5 2109.38     505 2108.03   508.4 2107.16
   512.92104.694   515.7 2103.75   521.1 2103.53   526.4 2103.71   530.2 2104.64
   533.9 2106.34   542.5  2111.6   547.9 2114.06   553.2 2114.99   561.7  2115.2
   578.4 2113.92     591 2114.52     616 2116.86   624.4 2118.16   637.4 2121.21
#Mann= 8 ,-1,0
       0     .06       0      30     .05       0     170     .06       0
     180     .05       0     320     .06       0   512.9    .045       0
   530.2     .06       0  583.97      .1       0
Bank Sta=512.9,530.2
XS Rating Curve= 0 ,0
Exp/Cntr(USF)=0,0
Exp/Cntr=0.3,0.1

Type RM Length L Ch R = 1 ,7063    ,44.9,44.8,46.1
XS GIS Cut Line= 4
 2270547.5677193629957.9257947872270848.84273468630268.970105933
2270914.48364978630312.7676197112270991.70156256630324.880233481
#Sta/Elev= 30
       0 2125.64    50.8 2120.22    81.4 2117.56     127 2114.94   161.9 2113.65
   182.7 2113.37   196.3  2112.5   216.1 2110.19   294.1 2109.91   317.1 2110.89
   356.3 2110.62   370.5 2109.63   393.1 2109.39   409.1 2107.14   429.9 2107.15
     437 2107.76   446.7 2106.97   467.3 2106.39   473.1 2105.46   481.52102.439
   485.1 2101.66   493.3 2101.52  500.51 2102.44   505.5 2103.88   511.9 2106.83
   514.6  2107.5   529.8 2109.12   538.3 2111.14   554.1 2112.16   590.1 2115.44
#Mann= 6 ,-1,0
       0     .05       0     110     .06       0     380     .07       0
     390     .06       0   481.5    .045       0  500.51     .06       0
Bank Sta=481.5,500.51
XS Rating Curve= 0 ,0
Exp/Cntr(USF)=0,0
Exp/Cntr=0.3,0.1

Type RM Length L Ch R = 1 ,7018    ,102.2,101.1,99.7
XS GIS Cut Line= 4
2270529.23032518629997.1955189842270822.81344424630300.330418726
2270881.42007726630344.9931538772270985.46456339630366.552651003
#Sta/Elev= 30
       0 2124.49    15.7 2122.96    44.5 2119.03      79 2116.53    96.2 2116.06
   116.9  2114.5   149.2 2113.33   178.2 2112.77     194 2111.85   211.2 2110.32
   236.9 2109.68   245.7 2109.07   272.8 2109.11   306.2 2108.27   356.4 2107.77
   400.9 2105.91   420.7 2106.15   449.8 2105.82   453.9 2105.14  462.38 2101.43
   469.6  2100.6   476.2 2100.81   481.12101.439   489.2 2102.26   518.5 2106.47
     523 2107.74     532 2111.61   539.3  2114.2   571.1 2121.59   601.9 2127.89
#Mann= 7 ,-1,0
       0     .05       0     130     .06       0     330     .07       0
     420     .06       0  462.38    .045       0   481.1      .1       0
  535.68     .06       0
Bank Sta=462.38,481.1
XS Rating Curve= 0 ,0
Exp/Cntr=0.3,0.1

Type RM Length L Ch R = 1 ,6917    ,134.6,135.5,136.4
XS GIS Cut Line= 2
2270461.34547802630220.2214812352270947.04149159630493.244941809
#Sta/Elev= 30
       0 2131.43    12.4 2126.29    35.4 2118.15    50.9 2114.23     118 2106.87
   140.8 2105.62   173.4 2105.87   209.7 2104.69   267.2 2105.01   308.8 2104.07
   372.9 2105.19   375.8 2104.77   387.12100.153   392.6 2098.86   397.9 2098.41
   402.5 2098.66   404.92099.913   408.1 2101.99   411.6 2103.35   434.6 2102.53
   439.2 2102.69   443.8 2103.82   450.9 2108.56     461 2119.07   467.2 2124.58
   489.6 2139.44   503.4 2146.41   525.6 2156.01   544.7 2163.97   557.2  2168.3
#Mann= 5 ,-1,0
       0     .05       0     300     .06       0   387.1    .045       0
   404.9     .06       0     410      .1       0
Bank Sta=387.1,404.9
XS Rating Curve= 0 ,0
Exp/Cntr(USF)=0,0
Exp/Cntr=0.3,0.1