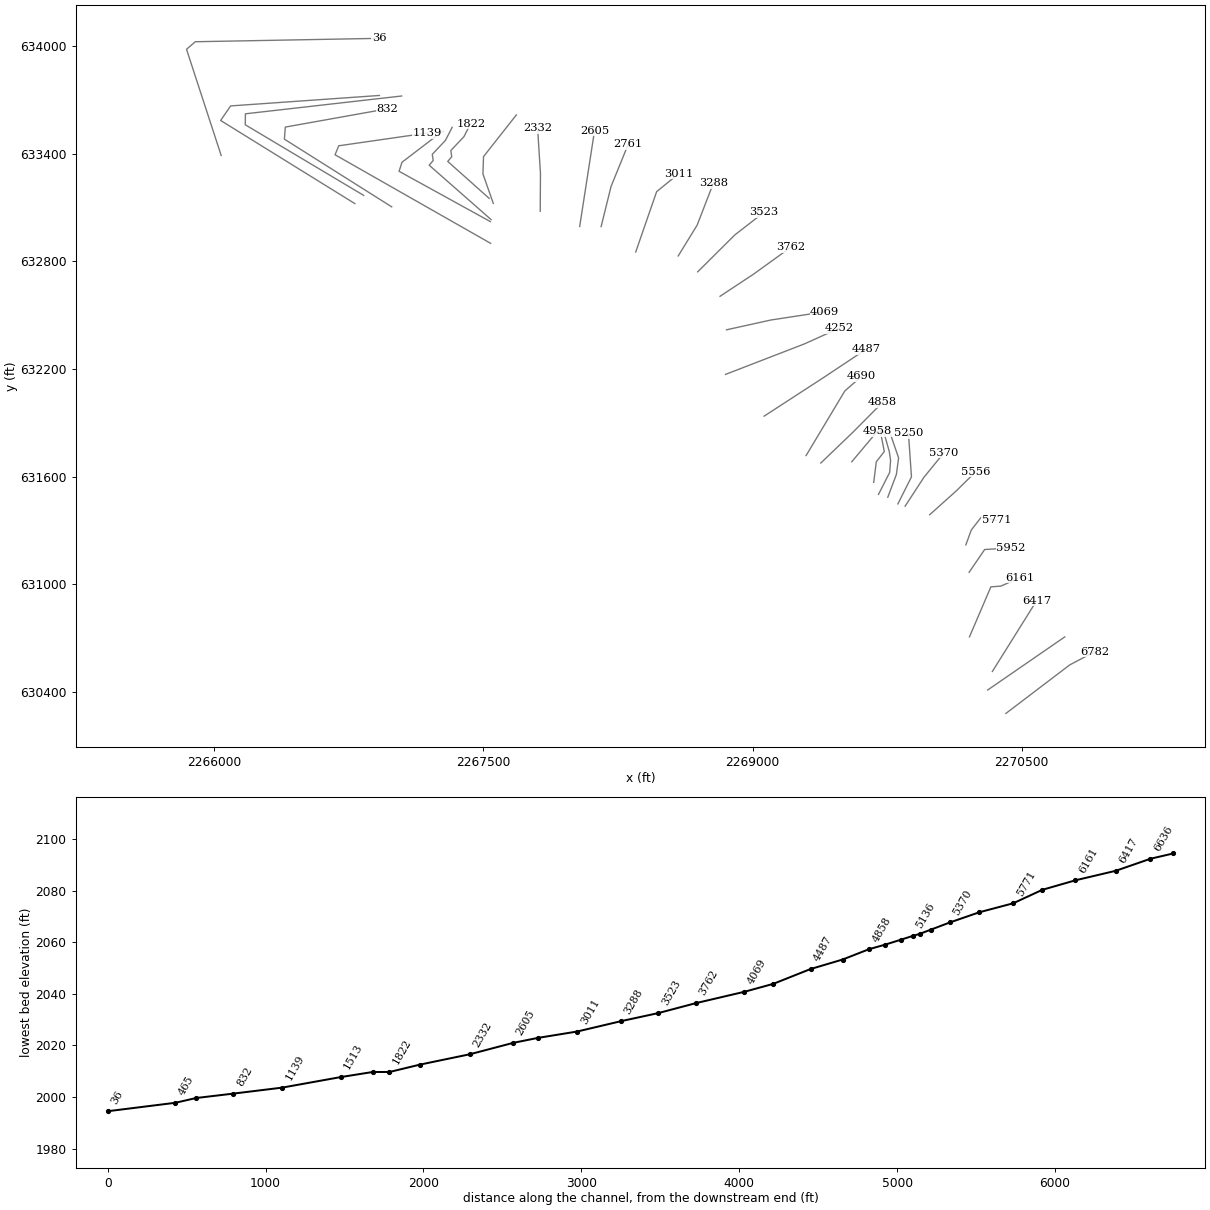
HEC-RAS study DRYRN.prj: DRYRN

--- DRYRN.g01 (geometry) --- (continued)

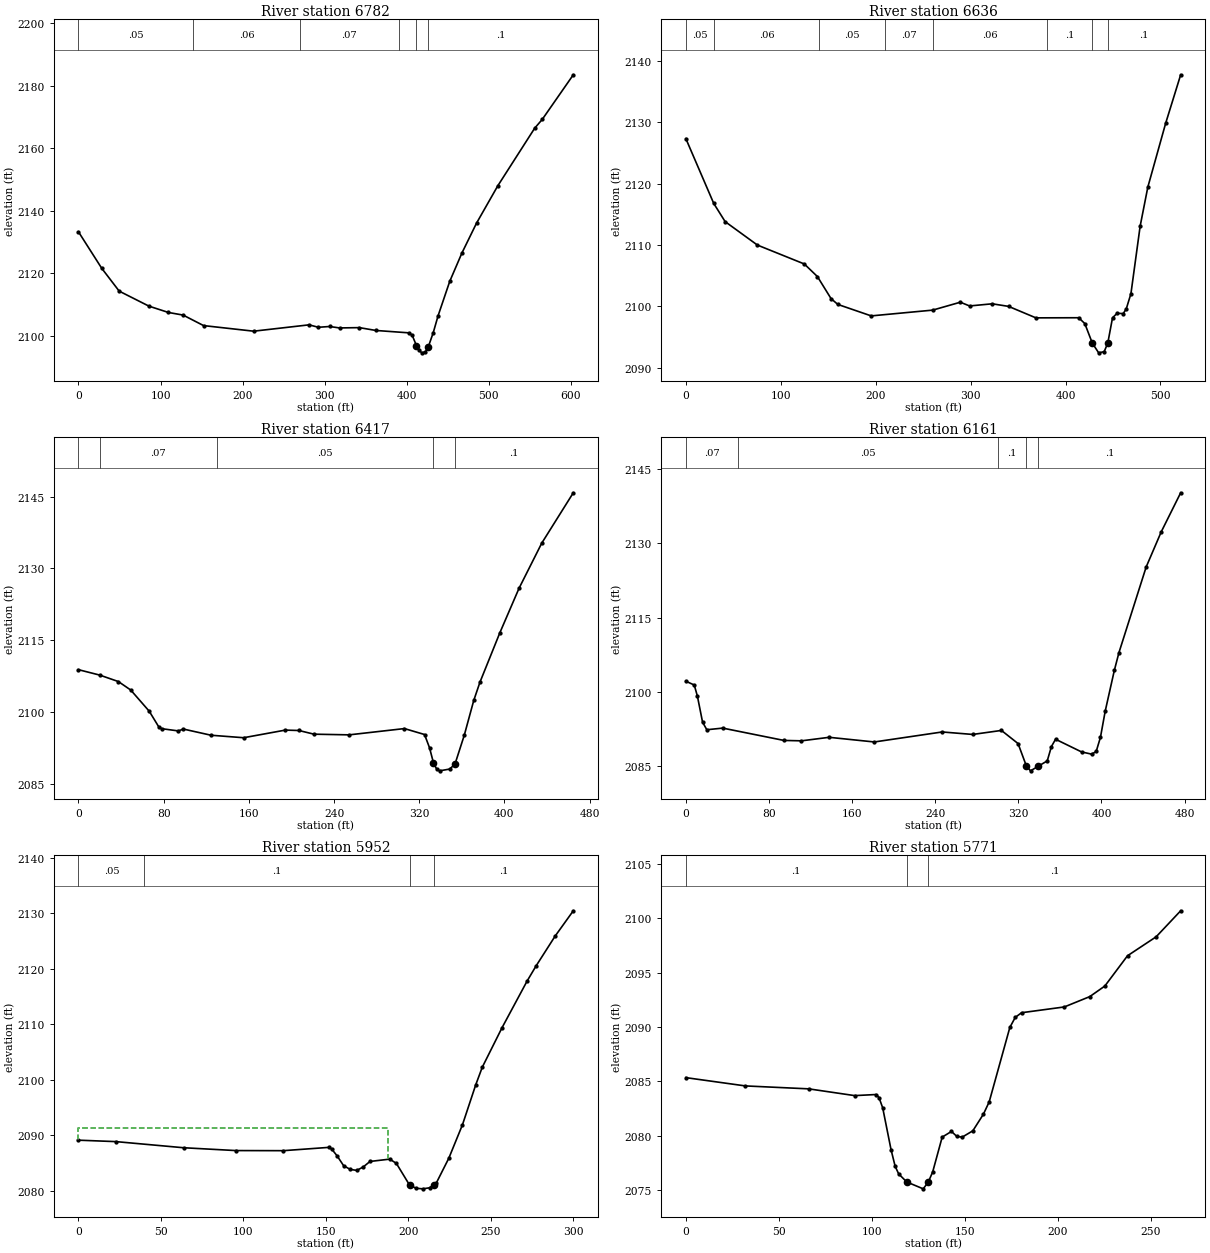
Type RM Length L Ch R = 1 ,6782    ,146,146,145.5
XS GIS Cut Line= 3
2270411.75234935630280.0390287452270767.38766938630550.360318812
2270905.50303559630623.052616815
#Sta/Elev= 30
       0 2133.22    28.3 2121.56    49.6 2114.24    85.9 2109.43   109.6 2107.41
   127.5 2106.57   152.4 2103.21   213.4 2101.42   280.9 2103.45   292.3 2102.67
   305.9 2102.92     318 2102.46   342.2 2102.56   362.3 2101.65   402.5 2100.89
   406.5 2100.13   411.72096.827     415 2095.26   418.3 2094.49   422.6  2094.8
   426.22096.442   432.2 2100.96   438.1 2106.37   452.3 2117.38   467.1 2126.43
   484.9 2135.99   510.9 2147.98   555.8  2166.4   564.9 2169.17   602.8 2183.48
#Mann= 6 ,-1,0
       0     .05       0     140     .06       0     270     .07       0
     390      .1       0   411.7    .045       0   426.2      .1       0
Bank Sta=411.7,426.2
XS Rating Curve= 0 ,0
Exp/Cntr(USF)=0,0
Exp/Cntr=0.3,0.1

Type RM Length L Ch R = 1 ,6636    ,214.3,218.9,221.7
XS GIS Cut Line= 2
2270310.05639897 630410.359571562270739.34921158630706.129528819
#Sta/Elev= 30
       0 2127.32    29.4 2116.75    41.4 2113.79    75.4 2109.97   124.8 2106.89
   138.6 2104.84     153 2101.24   160.1  2100.3   195.3 2098.43     260 2099.37
   289.2 2100.66   298.9 2100.05   322.8  2100.4     340 2099.98   368.8 2098.11
   413.9 2098.13   420.3 2097.18   428.2    2094   434.9 2092.41   440.7  2092.6
   444.52093.996   449.5 2098.12   454.3 2098.85   460.8 2098.81     464 2099.58
   468.9 2102.06   478.6 2113.05   486.7 2119.42   505.5 2129.83   521.3 2137.72
#Mann= 8 ,-1,0
       0     .05       0      30     .06       0     140     .05       0
     210     .07       0     260     .06       0     380      .1       0
   428.2    .045       0   444.5      .1       0
Bank Sta=428.2,444.5
XS Rating Curve= 0 ,0
Exp/Cntr(USF)=0,0
Exp/Cntr=0.3,0.1

Type RM Length L Ch R = 1 ,6417    ,260.5,255.7,247.4
XS GIS Cut Line= 2
2270336.04129581630513.6888909272270582.52245624630907.680577149
#Sta/Elev= 30
       0 2108.86      20 2107.73    37.5 2106.38    49.1 2104.61    66.5 2100.18
    75.2    2097    78.1 2096.55    93.8 2096.08    98.5 2096.47   124.5 2095.18
   155.1 2094.66   194.2 2096.25     207 2096.17   221.2  2095.4   254.2 2095.26
   306.1 2096.57     325 2095.33   329.7 2092.55   333.42089.398   336.4 2088.12
   339.1 2087.75   348.6 2088.12   353.62089.162   362.3 2095.17   371.2 2102.43
     377 2106.23   395.7 2116.55   413.8 2125.88   435.1 2135.28   464.7 2145.78
#Mann= 5 ,-1,0
       0     .06       0      20     .07       0     130     .05       0
   333.4    .045       0   353.6      .1       0
Bank Sta=333.4,353.6
XS Rating Curve= 0 ,0
Exp/Cntr(USF)=0,0
Exp/Cntr=0.3,0.1

Type RM Length L Ch R = 1 ,6161    ,210,210.1,209.8
XS GIS Cut Line= 4
2270208.36063729630706.4225474562270327.75643115630985.168771201
2270383.27062382630989.2307852982270490.47386282631036.757640175
#Sta/Elev= 30
       0 2102.16     8.1 2101.39    11.1 2099.16    16.1 2093.88    20.2 2092.36
    35.5 2092.69    94.4  2090.2   111.3 2090.12   137.9 2090.83   181.4 2089.89
   246.7 2091.91   276.1 2091.41   303.7 2092.22   319.7 2089.57   327.7 2085.05
   331.7 2084.06   339.3 2085.01   347.8 2086.07   351.8 2088.96   355.8 2090.44
   380.8 2087.88   390.5 2087.43   394.9 2087.97     399 2090.83   403.6 2096.14
   412.4 2104.38   416.8 2107.94     443 2125.23   457.5 2132.33   476.2 2140.21
#Mann= 5 ,-1,0
       0     .07       0      50     .05       0     300      .1       0
   327.7    .045       0   339.3      .1       0
Bank Sta=327.7,339.3
XS Rating Curve= 0 ,0
Exp/Cntr(USF)=0,0
Exp/Cntr=0.3,0.1

Type RM Length L Ch R = 1 ,5952    ,177.3,184.2,189
XS GIS Cut Line= 3
2270206.43804278631066.3252758892270293.01114253 631193.18735996
2270439.24503092631201.974604059
#Sta/Elev= 30
       0 2089.12    22.8 2088.86    63.7 2087.76    95.4 2087.25   124.2 2087.23
   152.1 2087.83   153.6 2087.51   156.8 2086.32   160.8 2084.53   164.8 2083.86
   168.8 2083.68   172.8 2084.32   176.8 2085.29   188.8 2085.71   192.8 2084.94
   200.8 2081.04   204.8 2080.46   208.9 2080.36   212.9 2080.55  215.35 2081.03
   216.9 2081.34   224.6 2085.87   232.9 2091.91   240.9 2099.06   244.9 2102.26
   256.9 2109.38   272.1 2117.78   277.5 2120.48   289.1 2125.87   300.1 2130.42
#Mann= 4 ,-1,0
       0     .05       0      40      .1       0   200.8    .045       0
  215.35      .1       0
#XS Ineff= 2 , 0
          187.51  2091.4
Permanent Ineff=
       F       F
Bank Sta=200.8,215.35
XS Rating Curve= 0 ,0
Exp/Cntr(USF)=0,0
Exp/Cntr=0.3,0.1

Type RM Length L Ch R = 1 ,5771    ,215.6,214.9,213.9
XS GIS Cut Line= 4
2270188.21379004631219.1174060082270218.58100125631301.972020692
2270273.52786595 631372.760740372270360.16901305 631355.57078602
#Sta/Elev= 30
       0 2085.35      32 2084.59    66.1 2084.32    90.8  2083.7   102.4  2083.8
   103.9 2083.52   105.9 2082.58   110.4 2078.73   112.6 2077.21   114.5 2076.51
  118.85 2075.77   127.7 2075.14  130.45 2075.77   132.8  2076.7   137.9 2079.89
   142.9 2080.41   145.8 2079.95   148.7 2079.89   154.4 2080.47   160.1    2082
   163.2 2083.13   174.3 2089.96   177.2 2090.88   180.6 2091.31   203.6 2091.84
   217.3 2092.79   225.4 2093.76   237.6 2096.54     253 2098.28   266.2 2100.67
#Mann= 3 ,-1,0
       0      .1       0  118.85    .045       0  130.45      .1       0
Bank Sta=118.85,130.45
XS Rating Curve= 0 ,0
Exp/Cntr(USF)=0,0
Exp/Cntr=0.3,0.1

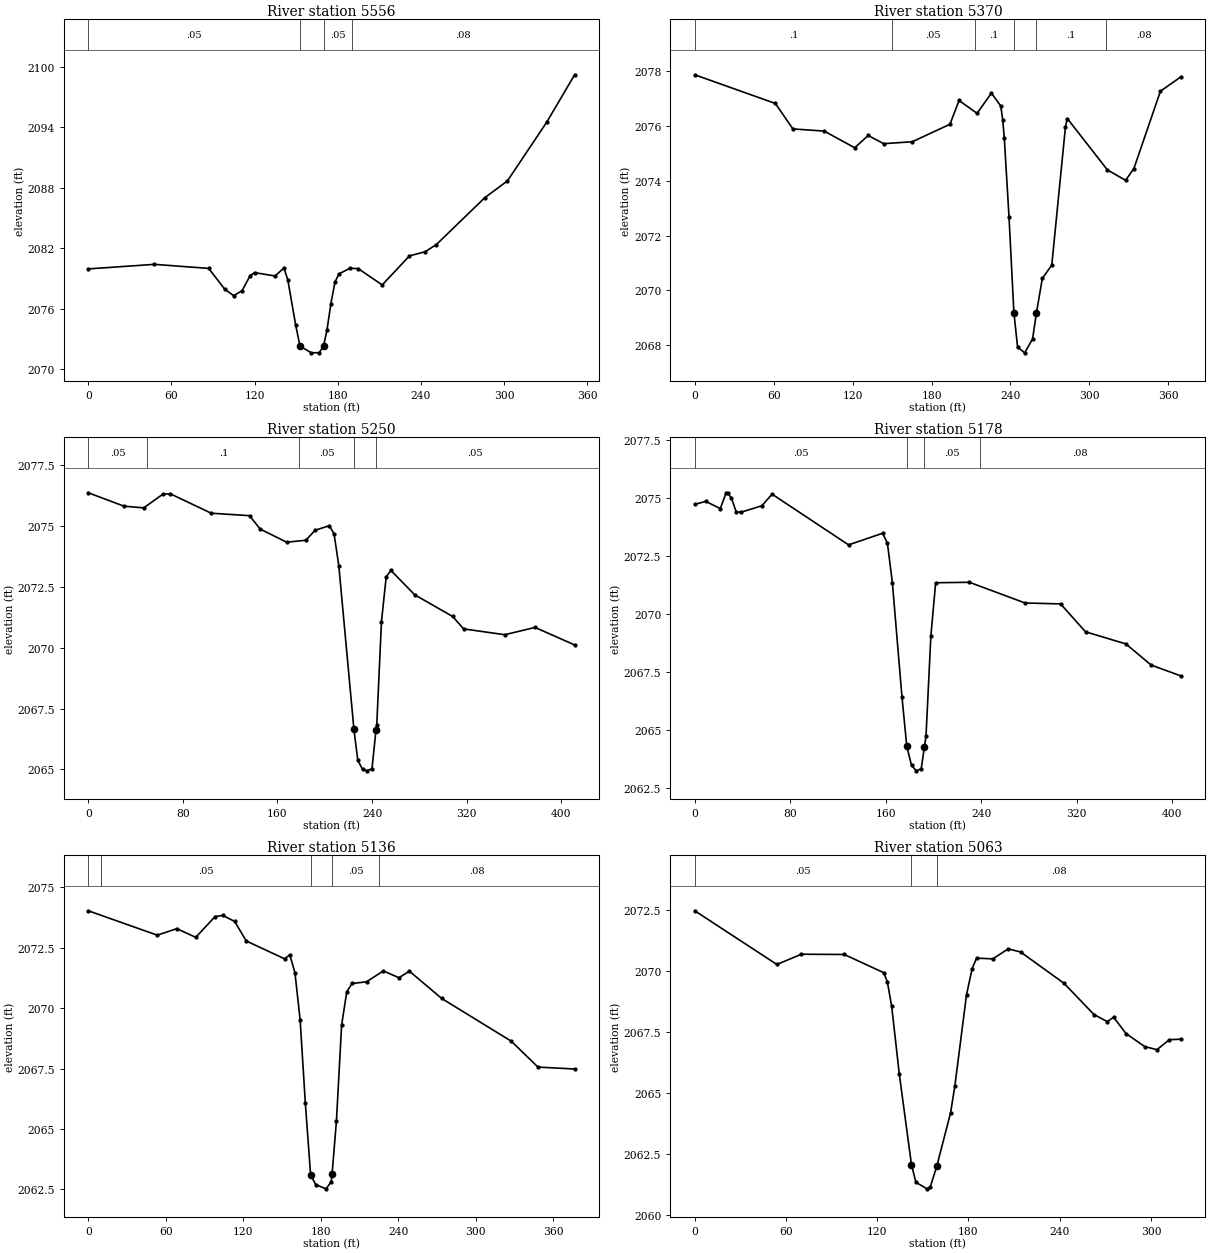
Type RM Length L Ch R = 1 ,5556    ,185.2,186,187.8
XS GIS Cut Line= 3
 2269986.8320233631387.1924980932270135.34215431631520.291200416
2270243.22215514631626.770162275
#Sta/Elev= 30
       0 2079.97    47.7 2080.42    86.9 2080.02    98.5 2077.95   104.9 2077.32
   110.9  2077.8   116.8 2079.29     120  2079.6   134.8 2079.27   141.2 2080.06
     144 2078.88   149.7 2074.38   152.8 2072.31     161 2071.65   166.7 2071.67
   169.8 2072.33   172.3 2073.94   175.1 2076.54     178 2078.64   180.8 2079.47
   188.8 2080.03   194.8    2080   212.1 2078.38   231.8 2081.26   243.1 2081.67
   251.2 2082.38   286.1 2087.02   302.5 2088.69   330.8  2094.5     351 2099.21
#Mann= 4 ,-1,0
       0     .05       0   152.8    .045       0   169.8     .05       0
     190     .08       0
Bank Sta=152.8,169.8
XS Rating Curve= 0 ,0
Exp/Cntr(USF)=0,0
Exp/Cntr=0.3,0.1

Type RM Length L Ch R = 1 ,5370    ,113.3,119.5,126.2
XS GIS Cut Line= 3
2269849.82525963631434.6889734822269954.96947638631596.190490418
2270066.84292301631733.298549066
#Sta/Elev= 30
       0 2077.88    61.3 2076.83    74.6  2075.9    98.4 2075.82   121.6 2075.21
   131.8 2075.66   143.6 2075.36   165.3 2075.43     194 2076.07   200.9 2076.94
   214.6 2076.47   225.5 2077.21   232.6 2076.74   234.1 2076.24   235.3 2075.56
   238.9 2072.67   242.6 2069.18   245.4 2067.92   250.8 2067.71   256.8 2068.22
   259.7 2069.16   264.2 2070.43   271.4 2070.92   281.8 2075.98   283.2 2076.28
   313.7  2074.4   327.5 2074.02   333.8 2074.45     354 2077.28   369.7 2077.81
#Mann= 6 ,-1,0
       0      .1       0     150     .05       0  212.71      .1       0
   242.6    .045       0   259.7      .1       0  312.71     .08       0
Bank Sta=242.6,259.7
XS Rating Curve= 0 ,0
Exp/Cntr(USF)=0,0
Exp/Cntr=0.3,0.1

Type RM Length L Ch R = 1 ,5250    ,74.6,72.9,71.5
XS GIS Cut Line= 3
2269809.44988039631447.3062794932269885.15371646631597.872797886
2269868.33064177631840.125073289
#Sta/Elev= 30
       0 2076.36    30.2 2075.81    46.9 2075.74      63  2076.3    69.3 2076.32
     104 2075.52   136.4 2075.42   145.4 2074.87   167.8 2074.33     184 2074.41
   191.9 2074.82   203.9 2075.01   207.9 2074.67   211.9 2073.37   224.7 2066.64
     228 2065.37     232    2065   235.7 2064.94     240 2065.03  243.36 2066.62
     244 2066.81     248 2071.07     252 2072.91     256 2073.17   276.1 2072.17
   308.2 2071.28   317.5 2070.77   352.3 2070.53   377.9 2070.83   411.4 2070.11
#Mann= 5 ,-1,0
       0     .05       0      50      .1       0  178.53     .05       0
   224.7    .045       0  243.36     .05       0
Bank Sta=224.7,243.36
XS Rating Curve= 0 ,0
Exp/Cntr(USF)=0,0
Exp/Cntr=0.3,0.1

Type RM Length L Ch R = 1 ,5178    ,40.7,41.1,41.6
XS GIS Cut Line= 4
2269753.25873404631484.5766591412269801.02795844631611.268949946
2269813.48949524 631703.692014552269755.33565684631872.961222758
#Sta/Elev= 30
       0 2074.71     9.2 2074.84    21.4 2074.53    26.3 2075.21    27.6  2075.2
    30.7 2074.98    34.8 2074.38    39.1 2074.38    56.2 2074.65    64.8 2075.15
   128.9 2072.97   157.5 2073.47   161.5 2073.03   165.6 2071.35   173.7 2066.41
   177.7  2064.3   181.7 2063.48   185.8 2063.25   189.8 2063.34  192.48 2064.29
   193.8 2064.74   197.9 2069.07   201.9 2071.34   230.2 2071.36   276.8 2070.47
   306.6 2070.43   327.5 2069.23   361.3 2068.71   382.5  2067.8   407.6 2067.33
#Mann= 4 ,-1,0
       0     .05       0   177.7    .045       0  192.48     .05       0
  238.66     .08       0
Bank Sta=177.7,192.48
XS Rating Curve= 0 ,0
Exp/Cntr(USF)=0,0
Exp/Cntr=0.3,0.1

Type RM Length L Ch R = 1 ,5136    ,77.1,73.3,67.7
XS GIS Cut Line= 5
2269701.33566403631500.1535801412269763.64334804631622.692025347
2269768.83565504 631690.192016352269761.56642524631738.999702152
2269728.33566043631856.345840357
#Sta/Elev= 30
       0 2074.03    53.4 2073.02    68.5 2073.29    83.2 2072.93    98.1 2073.79
     104 2073.84   113.3 2073.59   122.3 2072.78     152 2072.04     156 2072.21
     160 2071.46     164 2069.51     168 2066.09   172.1  2063.1   176.1 2062.69
   184.1 2062.52   188.1 2062.82   188.7 2063.12   192.1 2065.33   196.1 2069.29
   200.1 2070.68   204.2 2071.02   215.4 2071.09   228.4 2071.54   240.5 2071.26
   248.6 2071.53   273.6  2070.4   327.5 2068.63   348.1 2067.56   376.5 2067.48
#Mann= 5 ,-1,0
       0     .06       0      10     .05       0   172.1    .045       0
   188.7     .05       0  225.17     .08       0
Bank Sta=172.1,188.7
XS Rating Curve= 0 ,0
Exp/Cntr(USF)=0,0
Exp/Cntr=0.3,0.1

Type RM Length L Ch R = 1 ,5063    ,104.5,104.6,104.4
XS GIS Cut Line= 4
2269674.86528295 631567.591263462269689.16489642631681.988171289
2269733.74604433631739.1866252042269708.51143231631868.724300246
#Sta/Elev= 30
       0 2072.47      54 2070.27    70.1 2070.69    98.3 2070.68   124.4 2069.93
   126.7 2069.54   129.5 2068.55   134.5 2065.78   142.5 2062.07   145.4 2061.35
   152.7 2061.08   154.8 2061.14   159.2 2062.02   168.2 2064.19     171 2065.28
   178.7 2069.03   182.4  2070.1   185.3 2070.53     196  2070.5   206.1 2070.91
   214.3 2070.78   242.8  2069.5   262.5 2068.22   271.3 2067.93   275.4 2068.11
   283.6 2067.44   295.8 2066.91   303.9 2066.78   312.1 2067.19   319.8 2067.21
#Mann= 3 ,-1,0
       0     .05       0   142.5    .045       0   159.2     .08       0
Bank Sta=142.5,159.2
XS Rating Curve= 0 ,0
Exp/Cntr=0.3,0.1

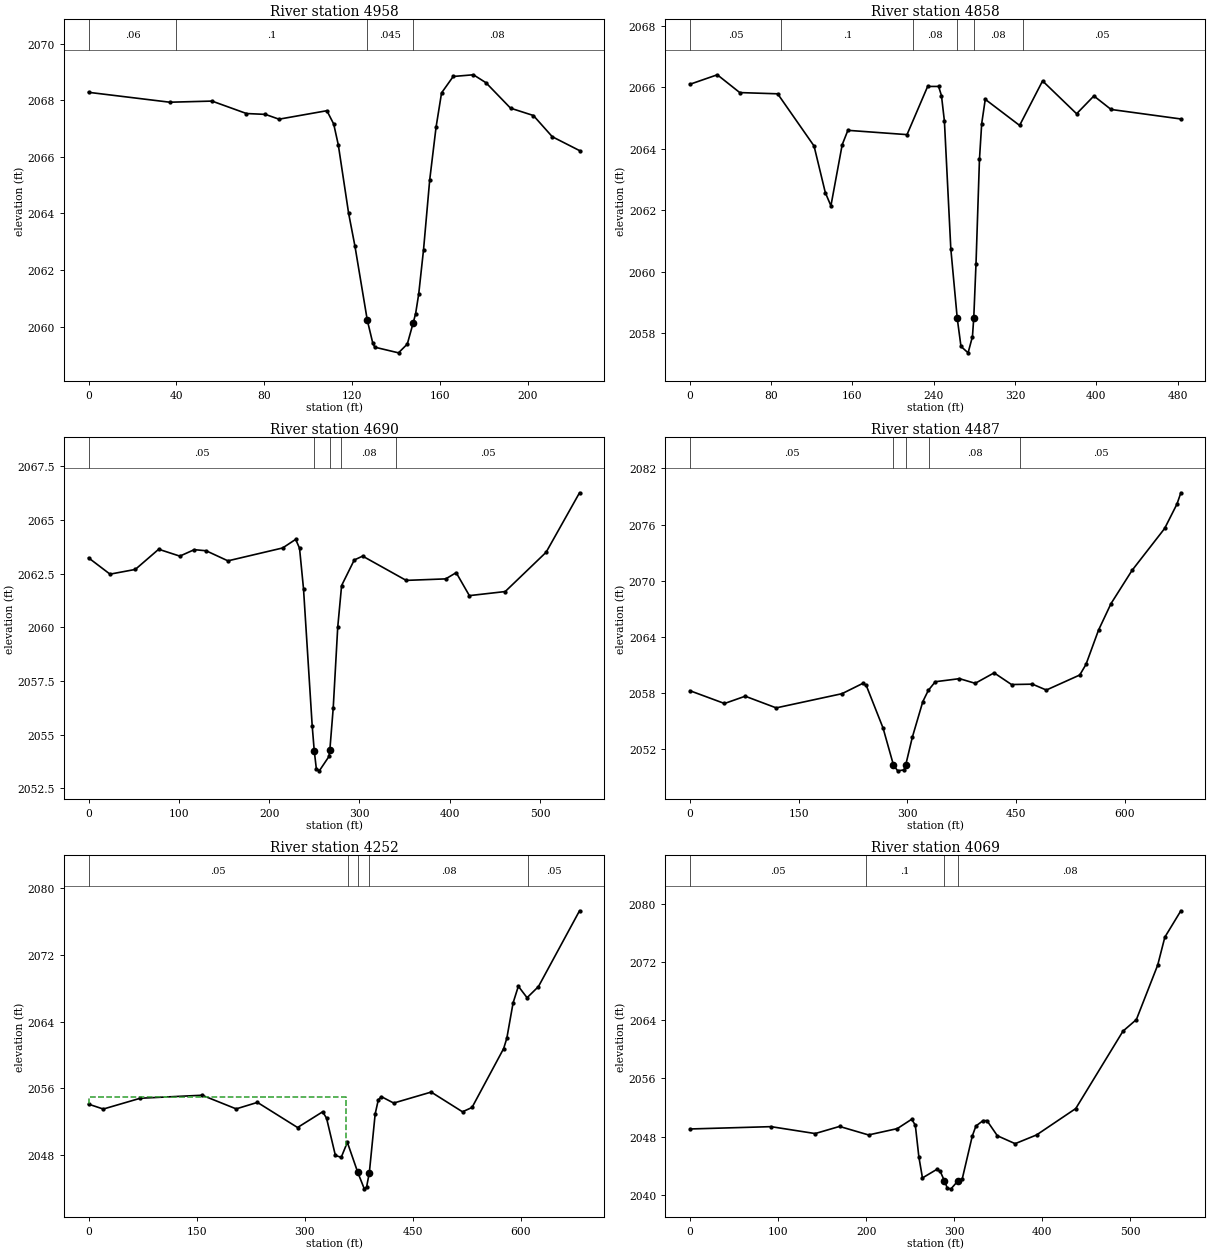
Type RM Length L Ch R = 1 ,4958    ,101.5,100.1,99.3
XS GIS Cut Line= 2
2269552.35591466631682.1470558842269696.19320318631853.237725387
#Sta/Elev= 30
       0 2068.28      37 2067.93    56.2 2067.97    71.9 2067.53    80.5  2067.5
    86.7 2067.33   108.5 2067.63   111.6 2067.16   113.7 2066.42   118.4    2064
   121.3 2062.83   126.9 2060.22   129.4 2059.41   130.3 2059.27   141.1 2059.07
   145.1 2059.38  147.82 2060.14   148.9 2060.46   150.3 2061.15   152.5 2062.72
   155.3 2065.18   158.2 2067.05   160.7 2068.26     166 2068.84   175.2  2068.9
   180.9 2068.62   192.1 2067.72   202.5 2067.46   211.1 2066.71   223.5 2066.22
#Mann= 4 ,-1,0
       0     .06       0      40      .1       0   126.9    .045       0
  147.82     .08       0
Bank Sta=126.9,147.82
XS Rating Curve= 0 ,0
Exp/Cntr(USF)=0,0
Exp/Cntr=0.3,0.1

Type RM Length L Ch R = 1 ,4858    ,167.2,168.4,171
XS GIS Cut Line= 3
2269379.99350997631675.2110116992269558.60887077631846.557142707
2269724.76269478632013.749428115
#Sta/Elev= 30
       0  2066.1      27 2066.41    49.1 2065.83    86.4 2065.79   122.2 2064.09
   133.3 2062.57   138.8 2062.14   149.9 2064.13   155.5  2064.6   213.7 2064.46
     234 2066.03   244.8 2066.03   247.6 2065.73   250.5  2064.9   256.8 2060.74
  263.14 2058.47   266.8 2057.56   273.8 2057.35   278.1 2057.88   279.4  2058.5
   281.6 2060.26     285 2063.66   287.2 2064.82   290.7 2065.61   324.5 2064.76
   347.1 2066.21   380.6 2065.14   397.6 2065.72   414.5 2065.28   483.2 2064.97
#Mann= 6 ,-1,0
       0     .05       0      90      .1       0     220     .08       0
  263.14    .045       0   279.4     .08       0  327.51     .05       0
Bank Sta=263.14,279.4
XS Rating Curve= 0 ,0
Exp/Cntr(USF)=0,0
Exp/Cntr=0.3,0.1

Type RM Length L Ch R = 1 ,4690    ,207.6,202.9,199.8
XS GIS Cut Line= 3
2269297.95505936631716.7494677012269513.95503057632077.095573517
2269607.41655658632158.095562721
#Sta/Elev= 30
       0 2063.23    23.8 2062.47    51.8 2062.69    77.7 2063.63   101.1 2063.31
   117.1 2063.61   130.2 2063.56   154.4 2063.09     215 2063.69   229.4 2064.09
   233.7 2063.68   238.1 2061.79   247.7 2055.42  249.97 2054.25   252.3 2053.41
   255.6 2053.31   266.3 2053.98   267.3  2054.3     271 2056.23     276    2060
   280.3 2061.94   294.3 2063.13   303.6 2063.31   351.8 2062.18   395.6 2062.25
   407.2 2062.54   421.8 2061.47   461.5 2061.66   506.8 2063.49   543.8 2066.26
#Mann= 5 ,-1,0
       0     .05       0  249.97    .045       0   267.3     .05       0
     280     .08       0     340     .05       0
Bank Sta=249.97,267.3
XS Rating Curve= 0 ,0
Exp/Cntr(USF)=0,0
Exp/Cntr=0.3,0.1

Type RM Length L Ch R = 1 ,4487    ,237.5,235.5,234
XS GIS Cut Line= 3
2269064.10893668631936.3391820222269396.07919262632152.045916494
2269630.77552782632308.134004261
#Sta/Elev= 30
       0 2058.21    47.8 2056.84    76.4 2057.62   119.2 2056.37     210 2057.89
   238.6 2058.99   243.4 2058.79   266.7 2054.21   281.1 2050.24   286.9 2049.63
   295.6 2049.73  297.89 2050.23   307.1 2053.23   321.6 2057.05   329.2 2058.25
   338.8 2059.17   372.2  2059.5   393.9    2059     420 2060.12     444 2058.87
   472.9 2058.91   492.1 2058.28   538.2 2059.89   546.8 2061.02   564.1 2064.69
   581.4 2067.54   610.3 2071.08   655.4 2075.58   672.4 2078.19   677.8  2079.4
#Mann= 5 ,-1,0
       0     .05       0   281.1    .045       0  297.89     .05       0
     330     .08       0   455.9     .05       0
Bank Sta=281.1,297.89
XS Rating Curve= 0 ,0
Exp/Cntr(USF)=0,0
Exp/Cntr=0.3,0.1

Type RM Length L Ch R = 1 ,4252    ,185.5,183.1,182.2
XS GIS Cut Line= 3
2268849.08853976632169.1599944112269287.83492003632338.675641333
2269480.14258671632425.570216645
#Sta/Elev= 30
       0 2054.07    20.5 2053.48    71.9 2054.78   157.7 2055.14   204.9  2053.5
   234.4 2054.28   290.1 2051.26   324.9 2053.15   330.3 2052.39   342.6  2047.9
   350.7 2047.68   359.2 2049.48   373.6 2045.88   382.7 2043.89   385.9 2044.11
   389.7 2045.84   397.8 2052.89   402.1 2054.57   406.4 2054.97   423.5  2054.2
   475.5 2055.52     519 2053.15   532.2 2053.67   576.1 2060.75   580.5 2061.99
   589.2 2066.24   596.5 2068.24   608.6 2066.86   624.4  2068.2   681.4 2077.31
#Mann= 5 ,-1,0
       0     .05       0     360     .08       0   373.6    .045       0
   389.7     .08       0  610.36     .05       0
#XS Ineff= 2 , 0
          357.32 2054.92
Permanent Ineff=
       T       F
Bank Sta=373.6,389.7
XS Rating Curve= 0 ,0
Exp/Cntr(USF)=0,0
Exp/Cntr=0.3,0.1

Type RM Length L Ch R = 1 ,4069    ,299.6,306.4,308.7
XS GIS Cut Line= 3
2268854.25636364632417.6064022112269101.55284963632472.150816732
2269402.12390963632518.054416995
#Sta/Elev= 30
       0 2049.04    92.1 2049.36   142.2 2048.41   169.9 2049.39   202.8 2048.22
   235.4 2049.09   251.8 2050.38   255.9 2049.55   259.9 2045.22     264 2042.31
   280.2 2043.48   284.2  2043.2  288.98  2041.9   292.3 2040.88   296.4 2040.81
   304.4 2041.92   309.1 2042.15   320.6 2048.09   324.7 2049.45   332.8 2050.19
   337.2 2050.19     349 2048.11   369.2 2047.02   393.5 2048.22     438 2051.85
   491.6 2062.49   506.8 2064.08     531 2071.57   539.1 2075.41   557.3 2079.04
#Mann= 4 ,-1,0
       0     .05       0     200      .1       0  288.98    .045       0
   304.4     .08       0
Bank Sta=288.98,304.4
XS Rating Curve= 0 ,0
Exp/Cntr=0.3,0.1

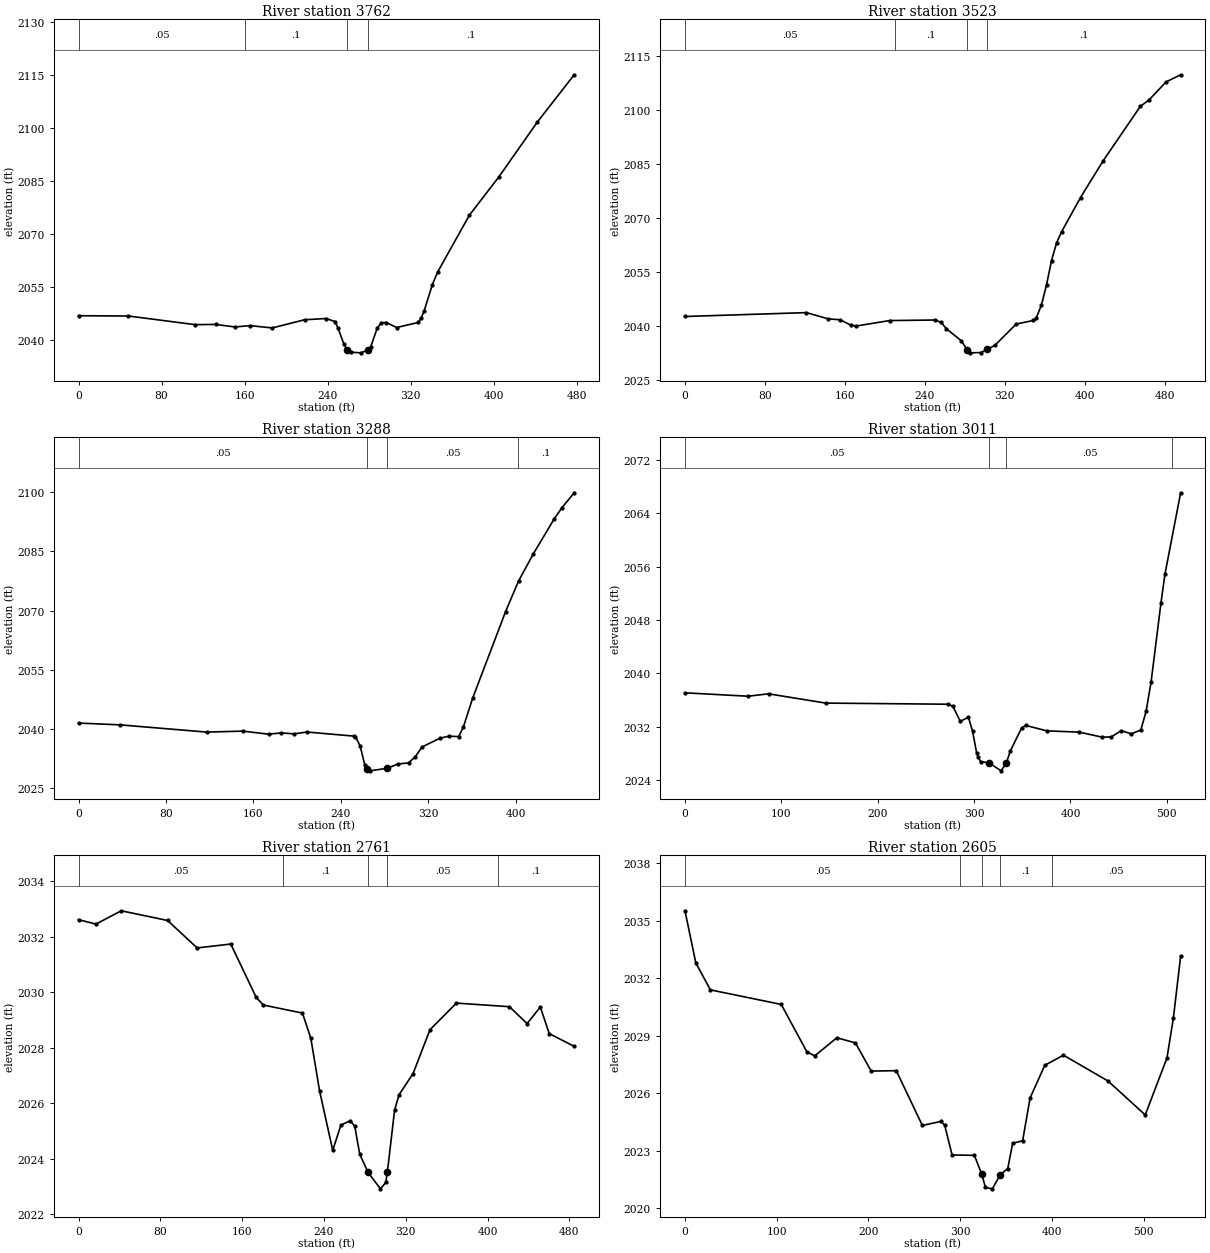
Type RM Length L Ch R = 1 ,3762    ,237.6,239.4,239.6
XS GIS Cut Line= 3
2268818.42600824 632604.308654362269006.28367551632728.612483946
2269210.96441746632876.281695032
#Sta/Elev= 30
       0 2046.93    48.1 2046.85   112.4  2044.4   132.1 2044.47   150.8 2043.75
   165.2 2044.13   186.6 2043.47   217.9 2045.79   238.5 2046.14   247.1 2045.29
   249.9 2043.53   255.7 2038.92   258.5 2037.31   262.1 2036.62     272 2036.42
   278.6 2037.17   281.5  2038.1   287.8 2043.38   291.7 2044.92   296.6 2045.01
   306.5 2043.59   327.3 2045.02   330.2 2046.28     333 2048.27     341 2055.77
     346 2059.28   376.6 2075.39   405.2 2086.31   441.9  2101.7   477.6 2115.17
#Mann= 4 ,-1,0
       0     .05       0     160      .1       0   258.5    .045       0
   278.6      .1       0
Bank Sta=258.5,278.6
XS Rating Curve= 0 ,0
Exp/Cntr(USF)=0,0
Exp/Cntr=0.3,0.1

Type RM Length L Ch R = 1 ,3523    ,232.7,235.8,241.3
XS GIS Cut Line= 3
 2268694.0029479632740.721456691     2268901.035      632946.636
2269062.24136036633071.575258746
#Sta/Elev= 30
       0 2042.65   121.5 2043.73   143.3    2042   155.4 2041.73   165.9 2040.23
   171.6 2040.01   204.8 2041.52   250.2 2041.67   256.4    2041   261.6 2039.24
   276.2 2035.96  282.32 2033.46   285.1 2032.54     296 2032.62   302.7 2033.48
   310.3 2034.68   331.4 2040.54   348.4 2041.54   351.6 2042.29   356.7 2045.83
   361.8 2051.45   366.8 2058.22   371.9 2063.18   376.9 2066.23   395.8 2075.74
   418.6 2086.02   455.7 2101.11   464.3 2102.87   481.4  2107.9     496 2109.89
#Mann= 4 ,-1,0
       0     .05       0     210      .1       0  282.32    .045       0
   302.7      .1       0
Bank Sta=282.32,302.7
XS Rating Curve= 0 ,0
Exp/Cntr=0.3,0.1

Type RM Length L Ch R = 1 ,3288    ,276.8,277,277.4
XS GIS Cut Line= 3
2268585.30831256632829.1359032012268690.91983695633001.105111049
2268781.57751717633235.693541319
#Sta/Elev= 30
       0 2041.51    37.6 2041.06   117.4 2039.22   150.3 2039.47   173.9 2038.69
   185.3 2039.02     197 2038.77     209 2039.24   252.3 2038.19   253.3 2038.07
   257.6 2035.67   261.9  2030.8  264.14 2029.99   266.2 2029.41   282.22030.043
   291.9 2031.12   301.8 2031.43     308 2032.97   314.2 2035.46   330.5 2037.67
   338.9 2038.19   347.7 2038.08     352 2040.54   360.6 2047.91   390.6 2069.75
   402.4 2077.45   416.1 2084.43   434.8 2093.11     442 2095.99   453.3 2099.82
#Mann= 4 ,-1,0
       0     .05       0  264.14    .045       0   282.2     .05       0
  401.81      .1       0
Bank Sta=264.14,282.2
XS Rating Curve= 0 ,0
Exp/Cntr(USF)=0,0
Exp/Cntr=0.3,0.1

Type RM Length L Ch R = 1 ,3011    ,249.9,249.9,249
XS GIS Cut Line= 3
2268348.49688104632851.2642029542268465.03834336633187.462222857
2268587.95308869633287.453336891
#Sta/Elev= 30
       0  2037.1    65.5 2036.59    86.7 2036.95     146 2035.56     273 2035.39
   277.9 2035.09   285.7 2032.82   294.1 2033.44   298.4 2031.34   302.6  2028.1
   304.3 2027.43   306.8 2026.76   315.52026.607     328  2025.4  333.54 2026.61
   337.6 2028.38   349.2  2031.8   353.4 2032.22   375.3  2031.4   409.3  2031.2
   433.2 2030.44   442.4  2030.5   452.7 2031.43     463 2030.95     473 2031.52
   478.5 2034.35   483.6 2038.68   493.9 2050.59     498 2054.87   514.3  2067.1
#Mann= 4 ,-1,0
       0     .05       0   315.5    .045       0  333.54     .05       0
  505.82      .1       0
Bank Sta=315.5,333.54
XS Rating Curve= 0 ,0
Exp/Cntr(USF)=0,0
Exp/Cntr=0.3,0.1

Type RM Length L Ch R = 1 ,2761    ,153.3,155.6,157.9
XS GIS Cut Line= 3
2268155.62495034632992.6113160692268211.00955835633216.457440079
2268306.77877635633451.842024089
#Sta/Elev= 30
       0 2032.62    17.1 2032.46    41.8 2032.94    87.1 2032.59     116  2031.6
   148.9 2031.74   173.7 2029.82   180.7 2029.54     219 2029.25   227.2 2028.34
   235.7 2026.45   248.6  2024.3   256.6 2025.21   265.9 2025.37   270.2 2025.16
     275 2024.16   283.2  2023.5   295.3 2022.91   300.5 2023.14  301.99  2023.5
   309.1 2025.75   313.4  2026.3   327.2 2027.07   343.7 2028.65   369.6 2029.61
   421.4 2029.48   438.7 2028.87   451.6 2029.47   460.3 2028.51   484.7 2028.05
#Mann= 5 ,-1,0
       0     .05       0     200      .1       0   283.2    .045       0
  301.99     .05       0   410.6      .1       0
Bank Sta=283.2,301.99
XS Rating Curve= 0 ,0
Exp/Cntr(USF)=0,0
Exp/Cntr=0.3,0.1

Type RM Length L Ch R = 1 ,2605    ,270.7,272.9,275.2
XS GIS Cut Line= 2
2268036.22876575632993.5567305652268119.04565573633527.386077325
#Sta/Elev= 30
       0 2035.52    11.8  2032.8    27.7 2031.39   104.9 2030.63   132.8 2028.16
   141.3 2027.94   165.6 2028.89   185.8 2028.62   202.9 2027.15   230.3 2027.17
   258.7 2024.31   278.9 2024.52     283 2024.33   291.1 2022.77   315.4 2022.75
   323.4 2021.77   327.5 2021.07     335    2021   343.7 2021.74   351.8 2022.06
   357.1 2023.38     368 2023.51   376.1 2025.74   392.1 2027.45   412.5 2027.98
   461.1 2026.63   501.6 2024.86   525.3 2027.83   532.3 2029.92   540.2 2033.15
#Mann= 5 ,-1,0
       0     .05       0     300      .1       0   323.4    .045       0
   343.7      .1       0     400     .05       0
Bank Sta=323.4,343.7
XS Rating Curve= 0 ,0
Exp/Cntr(USF)=0,0
Exp/Cntr=0.3,0.1

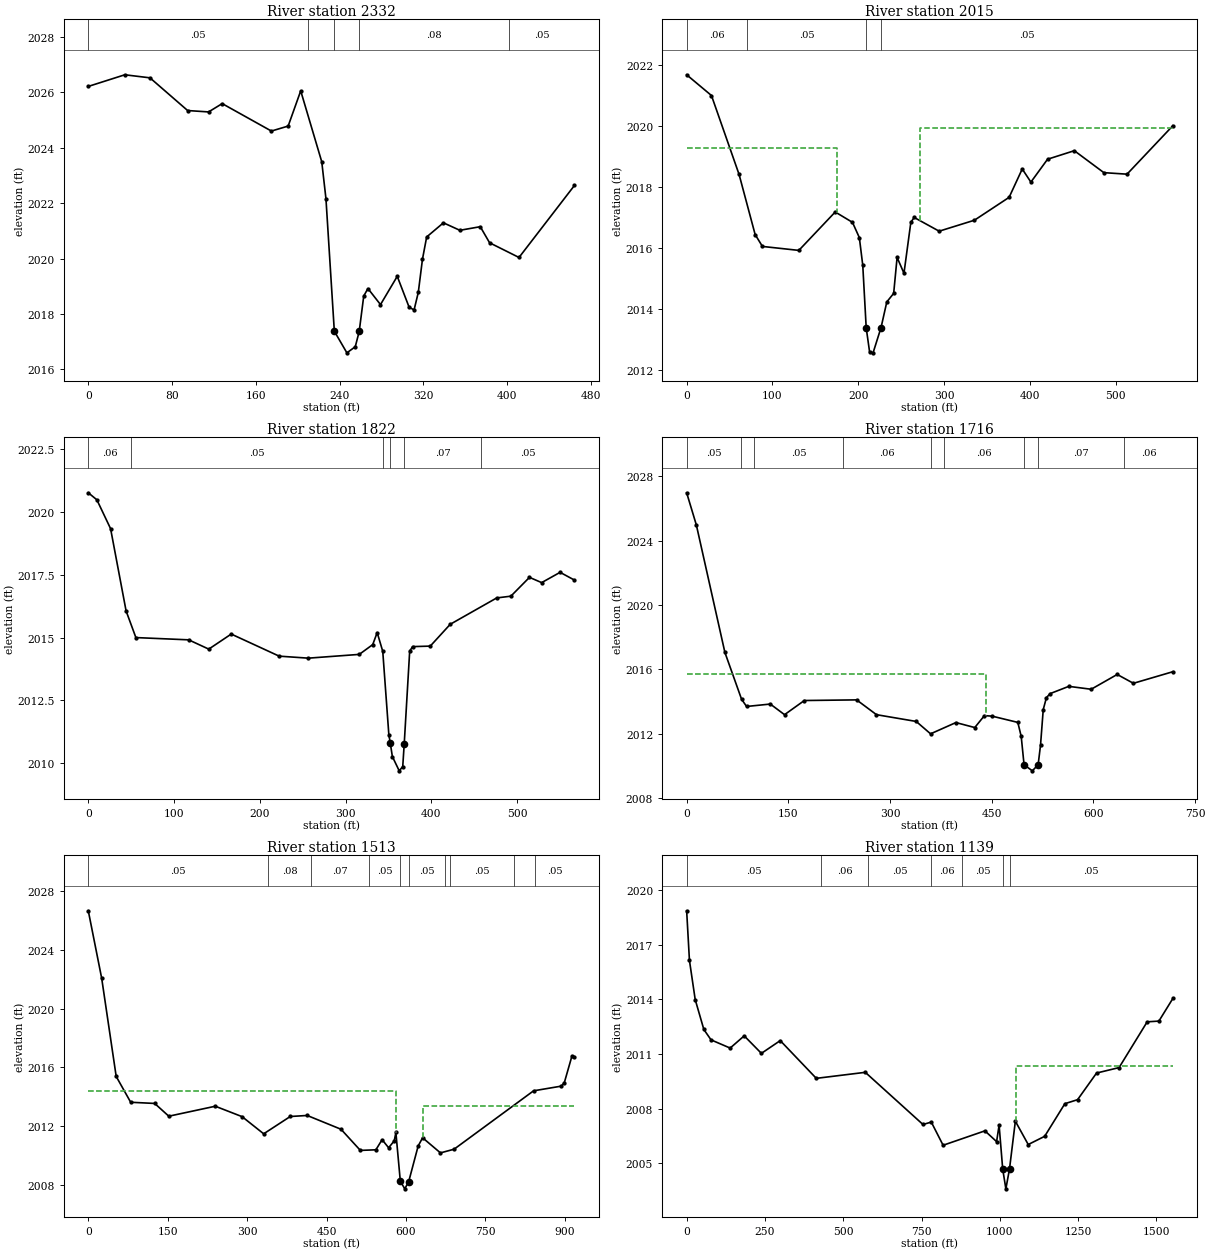
Type RM Length L Ch R = 1 ,2332    ,318.9,317.8,316.7
XS GIS Cut Line= 4
2267816.33724628633078.2333369462267817.61929739633289.771770288
2267804.79878628633491.053794741 2267802.3213351633542.184325896
#Sta/Elev= 30
       0 2026.21    34.9 2026.63    58.9 2026.52    94.9 2025.34   114.9 2025.29
   127.9 2025.59   174.9  2024.6   190.9 2024.78   202.9 2026.05     223 2023.49
     227 2022.16     235 2017.38     247  2016.6     255 2016.82  258.76 2017.37
   263.1 2018.65   267.1 2018.92   279.1 2018.34   295.1 2019.36   306.5 2018.24
   311.2 2018.15   315.2 2018.78   319.2 2019.98   323.2 2020.78   339.2 2021.29
   354.9 2021.02   374.4 2021.15   383.3 2020.57   411.4 2020.04   464.4 2022.64
#Mann= 5 ,-1,0
       0     .05       0     210     .08       0     235    .045       0
  258.76     .08       0  401.54     .05       0
Bank Sta=235,258.76
XS Rating Curve= 0 ,0
Exp/Cntr(USF)=0,0
Exp/Cntr=0.3,0.1

Type RM Length L Ch R = 1 ,2015    ,191.8,193.1,194.2
XS GIS Cut Line= 4
2267554.80445008 633121.872634352267497.14205056633285.907226385
 2267500.2802282  633382.76610532267683.22917237633615.108395661
#Sta/Elev= 30
       0 2021.68    28.9    2021    61.1 2018.41    79.8 2016.44    88.3 2016.05
   130.7 2015.92   173.1 2017.18   193.2 2016.84   201.2 2016.34   205.2 2015.43
   209.2 2013.38   213.2 2012.58   217.2 2012.56   226.5 2013.39   233.2 2014.23
   241.2 2014.51   245.2 2015.69   253.2 2015.17   261.2 2016.84   265.1    2017
   294.2 2016.55   335.3 2016.91   375.7 2017.66     391 2018.59   401.1 2018.16
   420.5 2018.91   451.7 2019.19   486.1 2018.47   513.1 2018.42   566.5 2020.01
#Mann= 4 ,-1,0
       0     .06       0      70     .05       0   209.2    .045       0
   226.5     .05       0
#XS Ineff= 2 , 0
          174.67 2019.29  272.02         2019.95
Permanent Ineff=
       T       F
Bank Sta=209.2,226.5
XS Rating Curve= 0 ,0
Exp/Cntr(USF)=0,0
Exp/Cntr=0.3,0.1

Type RM Length L Ch R = 1 ,1822    ,106,105.6,105.5
XS GIS Cut Line= 6
2267531.60827084 633150.31473569  2267300.884716633355.853064164
2267323.07775648633382.1226380972267318.06667182633416.573845103
2267391.41449481633494.3989694142267428.84993833633567.198197893
#Sta/Elev= 30
       0 2020.77      10 2020.49      26 2019.34    44.1 2016.06    55.5    2015
   117.1 2014.91   140.5 2014.54   166.7 2015.14   222.6 2014.26   256.6 2014.18
     316 2014.33   331.7 2014.72   336.9  2015.2   343.4 2014.45   350.5 2011.13
   352.2 2010.79   354.6 2010.26   362.6 2009.69   366.7 2009.86  368.44 2010.77
   374.8 2014.46   378.2 2014.64   398.8 2014.66   422.1 2015.53   476.3 2016.58
   492.8 2016.65   514.5  2017.4   528.7 2017.19   550.2  2017.6     567 2017.29
#Mann= 6 ,-1,0
       0     .06       0      50     .05       0  343.39     .07       0
   352.2    .045       0  368.44     .07       0   458.2     .05       0
Bank Sta=352.2,368.44
XS Rating Curve= 0 ,0
Exp/Cntr(USF)=0,0
Exp/Cntr=0.3,0.1

Type RM Length L Ch R = 1 ,1716    ,204.1,203.1,197.9
XS GIS Cut Line= 6
2267542.56449899 633031.714816172267197.61327004633334.746828284
2267219.80631051633361.0164022172267214.79522586633395.467609223
2267288.14304884633473.2927335342267325.57849236633546.091962013
#Sta/Elev= 30
       0 2026.98    14.3 2024.98    56.4 2017.06      81 2014.15    88.4  2013.7
   123.4 2013.85   144.4 2013.19   173.6 2014.07   250.7 2014.11     280 2013.19
   338.6 2012.77   359.8    2012   397.2  2012.7     425 2012.39   439.2 2013.13
   450.4  2013.1   488.5 2012.71   493.5 2011.84   497.7 2010.08   509.9  2009.7
  518.47 2010.08     522  2011.3     526 2013.51   530.7 2014.25   536.2  2014.5
   563.7 2014.95   596.7 2014.77   635.1 2015.69     659 2015.14   717.2 2015.86
#Mann= 9 ,-1,0
       0     .05       0      80     .06       0     100     .05       0
     230     .06       0     360     .08       0     380     .06       0
   497.7    .045       0  518.47     .07       0   645.3     .06       0
#XS Ineff= 2 , 0
          441.83 2015.71
Permanent Ineff=
       F       F
Bank Sta=497.7,518.47
XS Rating Curve= 0 ,0
Exp/Cntr(USF)=0,0
Exp/Cntr=0.3,0.1

Type RM Length L Ch R = 1 ,1513    ,374.1,373.2,371.8
XS GIS Cut Line= 4
2267538.30785826633020.655407443 2267029.6449419633300.935909352
2267045.95320574633351.3689035062267272.20955229633524.125349082
#Sta/Elev= 30
       0 2026.67    25.3 2022.07    52.7 2015.38    80.1 2013.62   125.4 2013.54
   152.1 2012.67   239.9 2013.35   290.5 2012.64   331.3 2011.47   381.5 2012.65
   413.5 2012.72   477.4 2011.78   513.9 2010.34   543.2 2010.38     555 2011.07
   567.3 2010.52   577.9 2010.99     581 2011.56   589.4 2008.24   597.8 2007.72
   605.2 2008.21   623.1 2010.64   631.5  2011.2   665.2 2010.17   690.9 2010.42
   841.1  2014.4   893.5 2014.72   899.2 2014.96   913.4 2016.75   918.4 2016.71
#Mann= 10 ,-1,0
       0     .05       0     340     .08       0     420     .07       0
     530     .05       0   589.4    .045       0   605.2     .05       0
  673.78     .07       0  683.78     .05       0  803.78     .07       0
  843.78     .05       0
#XS Ineff= 2 , 0
          581.12 2014.36     632         2013.35
Permanent Ineff=
       T       F
Bank Sta=589.4,605.2
XS Rating Curve= 0 ,0
Exp/Cntr(USF)=0,0
Exp/Cntr=0.3,0.1

Type RM Length L Ch R = 1 ,1139    ,303.9,306.8,308.9
XS GIS Cut Line= 4
2267539.91004423632899.4347035462266672.94281068633393.059323692
 2266693.4917741633443.0810259922267189.31244199633514.524158091
#Sta/Elev= 30
       0 2018.86     8.9 2016.14    27.3 2013.99    54.9 2012.35    77.9 2011.78
   138.9 2011.33   183.8    2012   238.7 2011.04   298.9 2011.74     414 2009.67
   570.5    2010   754.6 2007.14   781.3 2007.27     819    2006   952.5 2006.79
   989.8  2006.2   997.8  2007.1  1009.32004.694  1019.4 2003.61 1031.09 2004.71
  1049.7 2007.32  1090.8 2006.04  1143.3 2006.49  1207.8 2008.28  1248.4  2008.5
    1309 2009.96  1380.9 2010.26  1470.7 2012.77  1508.1 2012.81  1552.7 2014.05
#Mann= 7 ,-1,0
       0     .05       0     430     .06       0     580     .05       0
     780     .06       0     880     .05       0  1009.3    .045       0
 1031.09     .05       0
#XS Ineff= 2 , 0
                         1051.89         2010.32
Permanent Ineff=
       F       F
Bank Sta=1009.3,1031.09
XS Rating Curve= 0 ,0
Exp/Cntr(USF)=0,0
Exp/Cntr=0.3,0.1

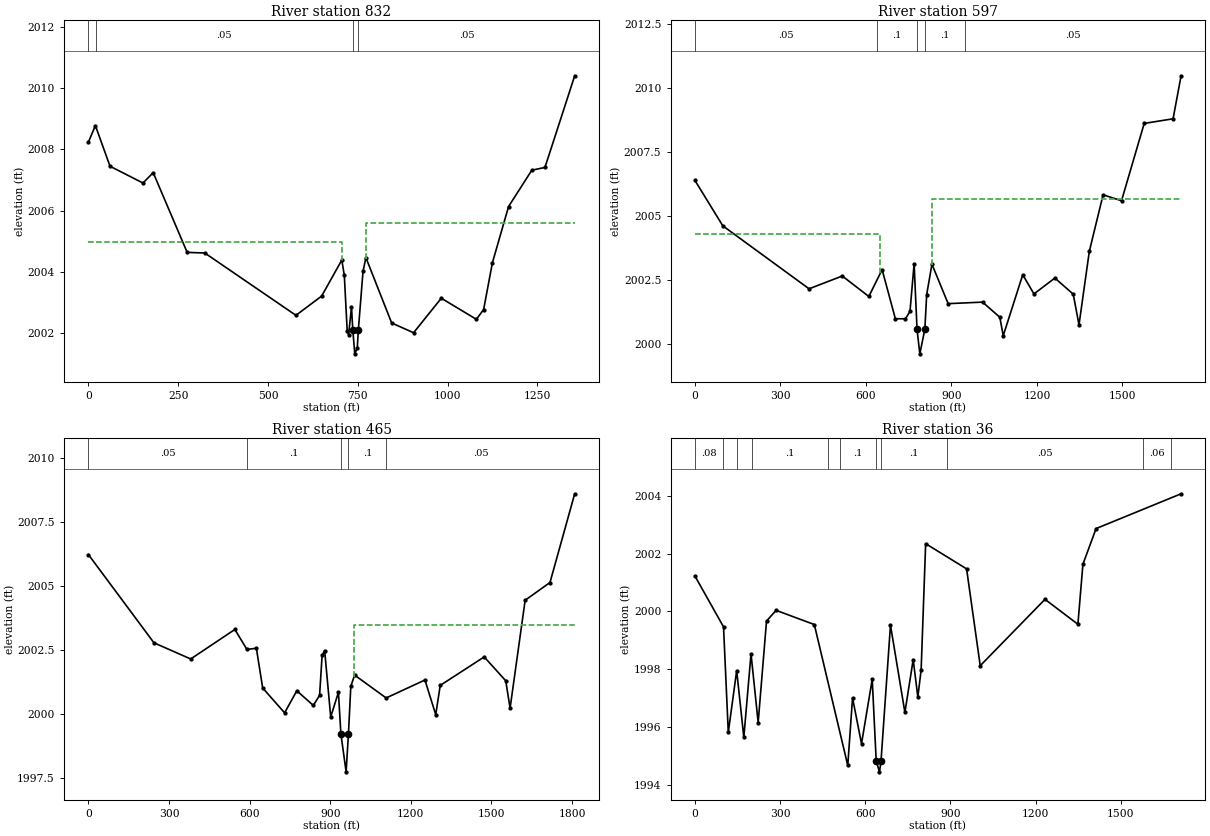
Type RM Length L Ch R = 1 ,832     ,235,235.6,240.1
XS GIS Cut Line= 4
2266988.67637844633102.8151080532266390.53675067633480.127963712
2266395.74752052633547.3216391112266965.67760499633649.372891828
#Sta/Elev= 30
       0 2008.24    19.4 2008.78    60.1 2007.45   151.9  2006.9   180.3 2007.24
   274.9 2004.63     324 2004.61   577.6 2002.57   649.2  2003.2   705.3 2004.38
   712.3 2003.88   720.3 2002.07   724.3 2001.94   732.3 2002.84     736 2002.08
   741.4 2001.31   748.4  2001.5   751.42002.096   764.4 2004.01   772.4 2004.46
   844.1 2002.32   905.1    2002   982.3 2003.13  1079.9 2002.44  1100.1 2002.76
  1124.5 2004.29  1169.5 2006.13  1234.2 2007.32  1270.8 2007.41  1353.6 2010.41
#Mann= 4 ,-1,0
       0     .06       0      20     .05       0     736    .045       0
   751.4     .05       0
#XS Ineff= 2 , 0
          705.69 2004.98  771.71          2005.6
Permanent Ineff=
       F       F
Bank Sta=736,751.4
XS Rating Curve= 0 ,0
Exp/Cntr(USF)=0,0
Exp/Cntr=0.3,0.1

Type RM Length L Ch R = 1 ,597     ,134.9,131.9,117.6
XS GIS Cut Line= 4
2266832.40250887633166.640331335 2266172.5776462633560.157113577
2266173.37038561633621.3386559432267044.08774017633720.518475214
#Sta/Elev= 30
       0 2006.38    98.1  2004.6   400.8 2002.14   517.2 2002.64   610.4 2001.84
     657 2002.89   703.5 2000.97     739 2000.97   754.8 2001.26   769.3 2003.12
   779.52000.552   789.3  1999.6   806.9 2000.56   813.3 2001.91   831.8  2003.1
   888.6 2001.56  1009.4 2001.62  1069.8 2001.03  1081.9 2000.31  1150.3 2002.69
  1189.6 2001.94    1263 2002.56  1327.5 2001.93  1347.6 2000.73  1383.8  2003.6
  1432.1 2005.81  1496.8 2005.58  1576.4  2008.6  1677.6 2008.78  1705.8 2010.46
#Mann= 5 ,-1,0
       0     .05       0     640      .1       0   779.5    .045       0
   806.9      .1       0  949.45     .05       0
#XS Ineff= 2 , 0
          649.76 2004.28  832.84         2005.64
Permanent Ineff=
       F       F
Bank Sta=779.5,806.9
XS Rating Curve= 0 ,0
Exp/Cntr(USF)=0,0
Exp/Cntr=0.3,0.1

Type RM Length L Ch R = 1 ,465     ,432.8,428.8,422.3
XS GIS Cut Line= 4
   2266783.54533633120.7590003782266035.27734855633584.181726733
2266090.87671701633665.2195486192266920.10398633633723.518951039
#Sta/Elev= 30
       0 2006.22   243.9 2002.78   380.6 2002.15     545  2003.3     590 2002.52
     625 2002.57   648.5 2001.02   730.1 2000.05   775.6 2000.91   836.8 2000.34
   860.3 2000.73   869.7 2002.29   879.1 2002.48   901.7 1999.89   930.4 2000.85
   939.6 1999.23     959 1997.75   967.8 1999.24   976.5 2001.09   990.8 2001.52
    1108 2000.63  1252.4 2001.33  1292.5 1999.98  1309.3 2001.12  1472.9 2002.23
  1553.1  2001.3  1569.2 2000.23  1625.3 2004.44  1717.7 2005.13  1809.7 2008.59
#Mann= 5 ,-1,0
       0     .05       0     590      .1       0   939.6    .045       0
   967.8      .1       0 1108.43     .05       0
#XS Ineff= 2 , 0
                          988.62         2003.47
Permanent Ineff=
       F       F
Bank Sta=939.6,967.8
XS Rating Curve= 0 ,0
Exp/Cntr(USF)=0,0
Exp/Cntr=0.3,0.1

Type RM Length L Ch R = 1 ,36      ,,,
XS GIS Cut Line= 4
2266038.31448832633389.0899949172265845.18328675633980.918153118
2265894.13937416634022.9517804392266919.61618862634041.896620586
#Sta/Elev= 30
       0 2001.23   101.1 1999.47   117.9 1995.83   147.4 1997.96   172.6 1995.66
   197.9 1998.54   223.1 1996.17   252.5 1999.67   286.2 2000.04   420.9 1999.55
   538.7 1994.69   555.5 1997.02   587.1 1995.44   624.8 1997.66   638.91994.838
   650.4 1994.47  655.76 1994.84   689.1 1999.53   739.9 1996.52   769.1 1998.34
   785.5 1997.05   797.1 1997.99     813 2002.34   957.2 2001.47  1005.2 1998.13
  1233.3 2000.42  1349.2 1999.56  1366.9 2001.63  1413.2 2002.86  1712.7 2004.06
#Mann= 11 ,-1,0
       0     .08       0     100      .1       0     150     .08       0
     200      .1       0     470     .05       0     510      .1       0
   638.9    .045       0  655.76      .1       0  887.07     .05       0
 1577.07     .06       0 1677.07     .05       0
Bank Sta=638.9,655.76
XS Rating Curve= 0 ,0
Exp/Cntr(USF)=0,0
Exp/Cntr=0.3,0.1
LCMann Table=0

Chan Stop Cuts=-1
Use User Specified Reach Order=0
Composite Channel Slope=5